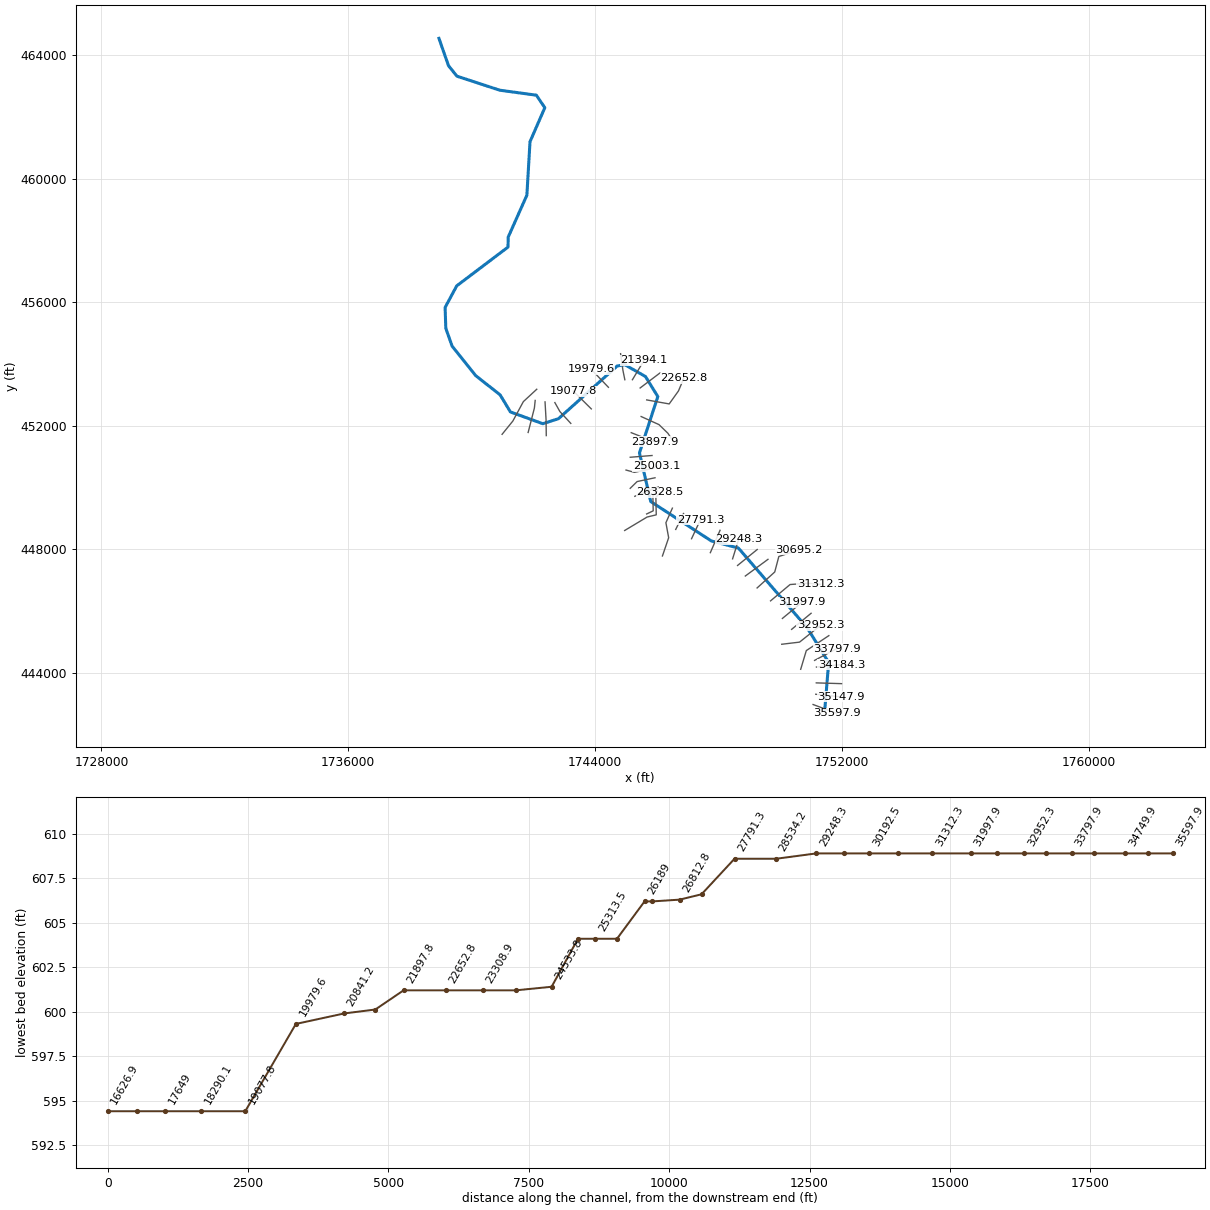
--- BIGCOALRIV.prj (project) ---

Proj Title=BIGCOALRIV
Current Plan=p01
Default Exp/Contr=0,0
English Units
Geom File=g01
Flow File=f01
Plan File=p01
BEGIN DESCRIPTION:
END DESCRIPTION:
DSS Export Rating Curves= 0
DSS Export Rating Curve Sorted= 0
DSS Export Volume Flow Curves= 0
DXF OffsetX= 0
DXF OffsetY= 0
DXF ScaleX= 0
DXF ScaleY= 0

--- BIGCOALRIV.p01 (plan) ---

Plan Title=Floodplain
Program Version=4.00
Geom File=g01
Flow File=f01
K Sum by GR=0
Std Step Tol=0.01
Critical Tol=0.01
Num of Std Step Trials=20
Max Error Tol=0.3
Flow Tol Ratio=0.001
Split Flow NTrial=30
Split Flow Tol=0.02
Split Flow Ratio=0.02
Log Output Level=0
Friction Slope Method=1
Unsteady Friction Slope Method=2
Unsteady Bridges Friction Slope Method=1
Global Log Level=0
CheckData=False
Run HTab=0
Run UNet=0
Run PostProcess=0
UNET Theta=0
UNET Theta Warmup=0
UNET ZTol=0
UNET ZSATol=0
UNET MxIter=0
UNET MaxInSteps=0
UNET DtIC=0
UNET DtMin=0
UNET MaxCRTS=0
UNET WFStab=0
UNET SFStab=0
UNET WFX=0
UNET SFX=0
UNET DSS MLevel=0
UNET DZMax Abort=0
UNET Convert EG Bridges=0
UNET Use Existing IB Tables=0
UNET Froude Limit=0
UNET Froude Power=0
Write IC File=0
Echo Input=False
Echo Output=False
Write Detailed=0

--- BIGCOALRIV.f01 (steady flow) ---

Flow Title=NFF Regression Equation
Program Version=4.10
Number of Profiles= 1
Profile Names=P100yr
River Rch & RM=BIGCOALRIV,Main            ,35597.9
32239.21
River Rch & RM=BIGCOALRIV,Main            ,22652.8
33893.27
River Rch & RM=BIGCOALRIV,Main            ,8721.2
33964.99
River Rch & RM=BIGCOALRIV,Main            ,116.3
34035.25
Boundary for River Rch & Prof#=BIGCOALRIV,Main            , 1
Up Type= 0
Dn Type= 3
Dn Slope=0.0003
DSS Import GetInterval= 0
DSS Import GetPeak= 0
DSS Import FillOption= 0

--- BIGCOALRIV.g01 (geometry) ---

Geom Title=USGS 10m DEM
Program Version=4.10

River Reach=BIGCOALRIV      ,Main
Reach XY= 30
     1751447.906      442816.914     1751573.705      444332.412
     1750885.328      445442.012     1748646.933      448037.857
     1747769.575      448267.802     1745805.122      449543.935
     1745439.494      451121.178     1746034.554      452944.606
     1745635.142      453593.223     1744963.789      453976.642
     1744717.753      453935.336     1742814.842       452228.47
     1742305.546        452065.3     1741255.814       452447.22
      1740921.43      453001.376     1740131.317      453622.517
     1739366.743      454576.897     1739161.319       455155.94
     1739139.291       455829.96     1739515.141      456530.706
     1741177.776      457786.022     1741185.067      458111.022
     1741789.677      459467.426     1741891.298      461200.907
      1742371.42      462301.513     1742097.143      462706.934
     1740911.379      462868.393     1739520.785      463323.292
      1739249.39      463661.691     1738939.171      464548.708

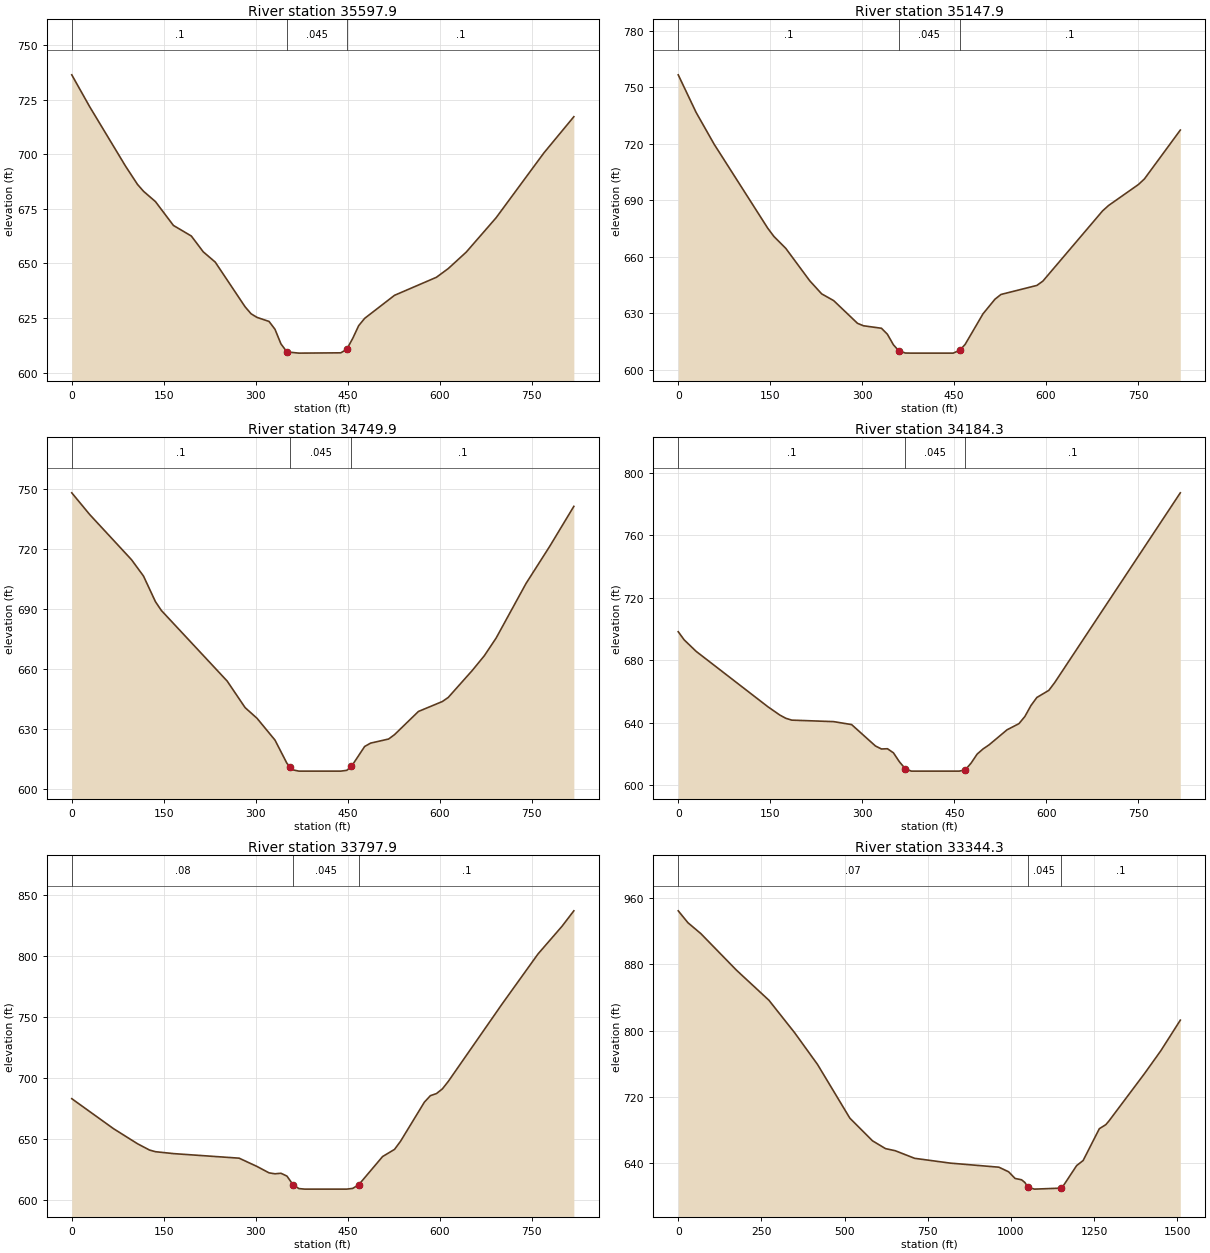
Type RM Length L Ch R = 1 ,35597.9 ,433.3,450,466.7
XS GIS Cut Line= 3
     1751067.914      442969.873     1751451.413      442826.279
     1751834.911      442682.685
#Sta/Elev= 30
       0   736.4    29.2  721.79    87.8  694.53   107.2  686.21     117  683.06
   136.5  678.32   165.8   667.4     195  662.56   214.5   655.3     234  650.61
   282.8   630.1   292.5  626.92   302.2  625.27   321.8  623.42   331.5  619.83
   341.2  613.14     351  609.45   370.5   608.9   438.8  609.04   448.5  610.62
   458.2  615.59     468  621.47   477.8  624.83   526.5  635.39   594.8  643.64
   614.2  647.65   643.5  655.19   692.2  670.92   770.2  700.65     819  717.21
#Mann= 3 , 0 , 0
       0      .1       0     351    .045       0   448.5      .1       0
Bank Sta=351,448.5
XS Rating Curve= 0 ,0
Exp/Cntr=0.3,0.1

Type RM Length L Ch R = 1 ,35147.9 ,393.4,398,402.6
XS GIS Cut Line= 3
     1751154.797      443301.863     1751562.196      443260.434
     1751969.595      443219.005
#Sta/Elev= 30
       0  756.51    29.2  736.55    58.5  719.75   146.2  675.07     156  670.82
   175.5  664.44   214.5  647.28     234  640.33   253.5  636.77   292.5  624.69
   302.2  623.41   331.5  622.09   341.2  618.92     351  613.33   359.5  610.22
   370.5  608.95   380.2   608.9   448.5   608.9   459.5  610.47     468  613.54
   497.2  629.77   516.8  637.55   526.5  640.02     585  644.81   594.8  647.09
   692.2  684.34     702  687.21   750.8  698.36   760.5  701.31     819  727.21
#Mann= 3 , 0 , 0
       0      .1       0   359.5    .045       0   459.5      .1       0
Bank Sta=359.5,459.5
XS Rating Curve= 0 ,0
Exp/Cntr=0.3,0.1

Type RM Length L Ch R = 1 ,34749.9 ,557.2,565.6,574.1
XS GIS Cut Line= 3
     1751171.009       443670.51     1751580.318      443657.998
     1751989.627      443645.487
#Sta/Elev= 30
       0  748.26    29.2  737.41    97.5  714.76     117  706.58   136.5  693.75
   146.2  689.33   253.5     654   282.8  640.68   302.2  635.36   331.5  624.44
     351   612.8   356.2  611.06   360.8  609.53   370.5   608.9   438.8   608.9
   448.5  609.28   456.2  611.25   477.8  621.25   487.5  622.93   516.8  624.97
   526.5  627.17   565.5  638.78   604.5  643.75   614.2  645.82   653.2  659.27
   672.8  666.61   692.2  675.52     741  702.87     780  721.64     819  741.49
#Mann= 3 , 0 , 0
       0      .1       0   356.2    .045       0   456.2      .1       0
Bank Sta=356.2,456.2
XS Rating Curve= 0 ,0
Exp/Cntr=0.3,0.1

Type RM Length L Ch R = 1 ,34184.3 ,361.1,386.4,411.6
XS GIS Cut Line= 2
     1751176.862      444182.876     1751991.269      444264.086
#Sta/Elev= 30
       0  698.29     9.7  693.07    29.2   685.7   146.2  650.16   165.6  644.86
   175.4  642.78   185.1   641.6   253.3  640.64   282.6  638.75   321.5  625.02
   331.3   623.1     341  623.26   350.8  620.63   360.5  614.91   370.2  610.38
     380   608.9   457.9   608.9   467.7  609.64   477.4  614.06   487.2  619.81
   496.9  623.14   506.7  625.75   535.9  635.38   555.4  639.35   565.1  643.97
   574.9  650.94   584.6  656.14   604.1   660.7   613.8  665.77   818.4  787.36
#Mann= 3 , 0 , 0
       0      .1       0   370.2    .045       0   467.7      .1       0
Bank Sta=370.2,467.7
XS Rating Curve= 0 ,0
Exp/Cntr=0.3,0.1

Type RM Length L Ch R = 1 ,33797.9 ,447.2,453.6,460
XS GIS Cut Line= 3
     1751115.958      444398.997     1751477.869      444590.597
      1751839.78      444782.197
#Sta/Elev= 30
       0  683.06    68.2  658.44   107.2  646.12   126.8  640.95   136.5  639.59
   165.8  638.03     273  634.28   302.2  627.48   321.8  622.25   331.5  621.47
   341.2  621.92     351  619.59   360.8  612.58   370.5  609.34   380.2   608.9
   448.5   608.9   458.2  609.49     468  612.44     507   635.6   526.5  641.49
   536.2  648.08   575.2  680.22     585  685.54   594.8  687.23   604.5  691.07
   614.2  697.24     702  760.72   760.5   801.7   799.5  824.31     819   837.1
#Mann= 3 , 0 , 0
       0     .08       0   360.8    .045       0     468      .1       0
Bank Sta=360.8,468
XS Rating Curve= 0 ,0
Exp/Cntr=0.3,0.1

Type RM Length L Ch R = 1 ,33344.3 ,386.3,392,397.7
XS GIS Cut Line= 3
     1750665.958      444110.602      1750848.25      444716.505
     1751578.654      445200.785
#Sta/Elev= 30
       0  944.42    29.2  930.06    68.1  916.89   175.2  872.81   272.6  836.62
   350.4  797.17   418.6  759.25   515.9  694.44   584.1   667.1     623  657.73
   652.2  655.21   710.6  646.04   817.7  640.25   963.8  635.34     993   629.8
  1012.5  621.78    1032  620.15  1041.7  616.99  1051.4  611.18  1070.9   608.9
  1149.6  610.08  1158.6  613.64  1197.5  637.28    1217  643.38  1265.7  681.74
  1285.1   686.6  1294.9  691.21    1402  748.49  1450.7  775.85  1509.1   812.6
#Mann= 3 , 0 , 0
       0     .07       0  1051.4    .045       0  1149.6      .1       0
Bank Sta=1051.4,1149.6
XS Rating Curve= 0 ,0
Exp/Cntr=0.3,0.1

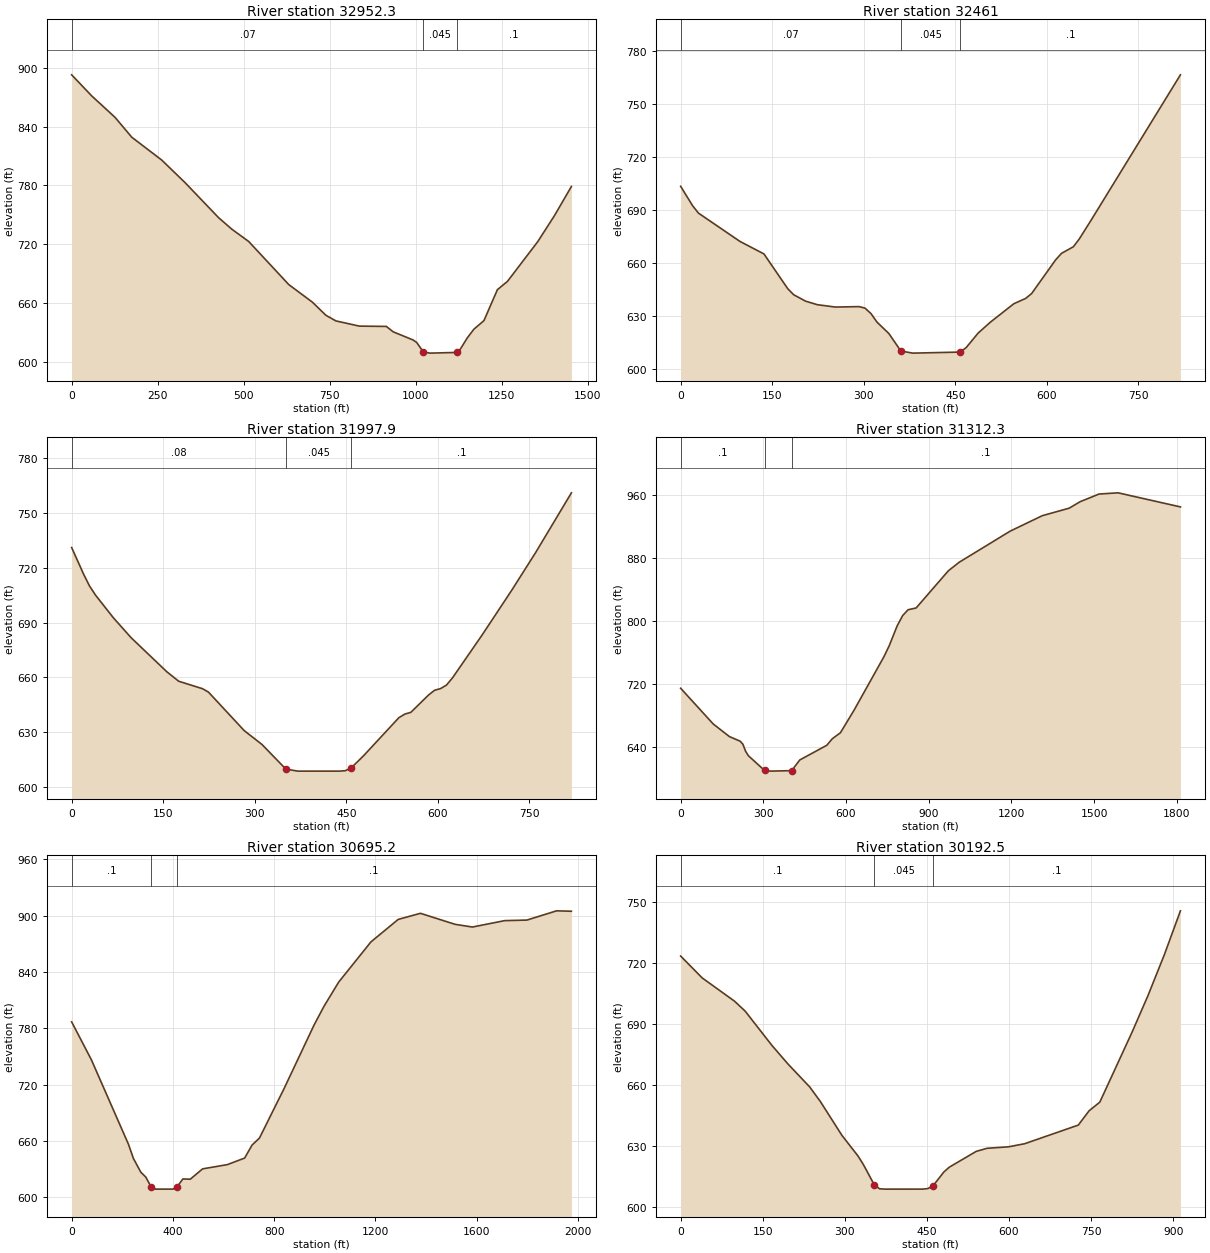
Type RM Length L Ch R = 1 ,32952.3 ,490.2,491.3,492.4
XS GIS Cut Line= 3
     1750051.375      444921.366       1750629.5       444990.81
     1751310.087       445533.27
#Sta/Elev= 30
       0  892.95    58.2  871.48   126.2  849.53   174.7   829.3     262   805.9
     330  782.79     427  747.18   465.8  735.32   514.4  722.92   631.2  678.83
   699.6  660.96   738.7  647.61   768.1  641.77   836.5  636.46   914.8  636.16
   934.3   630.7     993  622.23  1002.8   619.8  1022.3  610.08  1041.9   608.9
  1120.1  609.61  1129.9  613.05  1149.5  624.22    1169  633.26  1198.4   642.1
  1237.5  673.68  1266.8  682.16  1354.8   722.7  1403.7  749.44  1452.6  779.01
#Mann= 3 , 0 , 0
       0     .07       0  1022.3    .045       0  1120.1      .1       0
Bank Sta=1022.3,1120.1
XS Rating Curve= 0 ,0
Exp/Cntr=0.3,0.1

Type RM Length L Ch R = 1 ,32461   ,463.1,463.1,463
XS GIS Cut Line= 3
     1750371.714      445404.056     1750687.671      445664.559
     1751003.414       445925.32
#Sta/Elev= 30
       0  703.49    19.5  692.53    29.2  688.29    97.5  672.18   136.5  665.15
   175.5  645.44   185.2  642.02   204.8  638.36   224.2  636.35   253.5  635.03
   292.5  635.27   302.2  634.41     312  631.27   321.8  626.46   341.2  620.02
   360.8  610.12   380.2   608.9   458.2  609.49     468  612.08   487.5  620.26
     507   626.3     546  636.91   565.5  639.95   575.2  642.71   614.2  661.64
     624  665.45   643.5  669.21   653.2  673.61   672.8  684.38     819  766.72
#Mann= 3 , 0 , 0
       0     .07       0   360.8    .045       0   458.2      .1       0
Bank Sta=360.8,458.2
XS Rating Curve= 0 ,0
Exp/Cntr=0.3,0.1

Type RM Length L Ch R = 1 ,31997.9 ,685.2,685.6,686.1
XS GIS Cut Line= 3
     1750073.294      445758.205     1750389.251      446018.708
     1750705.207      446279.211
#Sta/Elev= 30
       0  730.91    19.5  716.46    29.2     710      39  705.02    68.2  692.66
    97.5   681.7     156  663.12   175.5  657.95   214.5  653.88   224.2  652.03
   282.8  631.01     312  623.42     351  610.02   370.5   608.9   438.8   608.9
   448.5  609.12   458.2  610.71   477.8  617.08   536.2  638.05     546  640.03
   555.8  640.97     585  650.48   594.8  653.04   604.5  653.93   614.2  655.86
     624  659.74   672.8  683.27   721.5  707.78   760.5  728.26     819  760.79
#Mann= 3 , 0 , 0
       0     .08       0     351    .045       0   458.2      .1       0
Bank Sta=351,458.2
XS Rating Curve= 0 ,0
Exp/Cntr=0.3,0.1

Type RM Length L Ch R = 1 ,31312.3 ,614.5,617.1,619.6
XS GIS Cut Line= 4
     1749688.919      446326.693     1750321.731      446856.207
     1750895.125      446899.144     1751306.632      446860.938
#Sta/Elev= 30
       0  714.18   117.9  668.89   176.8   652.8   216.1   646.9   225.9  643.02
   235.8  633.99   245.6  628.51   304.5  609.74   324.2   608.9   402.7   609.5
   432.2  623.07   530.4  641.77   550.1  650.01   579.6  657.63   628.7  686.01
   736.7  753.67   756.4  767.92   785.8  793.61   805.5  806.47   825.1  813.89
   854.4  816.17   971.3  863.38  1010.3  874.16  1195.5  913.75  1312.4  933.43
    1410  942.97  1449.3  951.14  1518.2   960.9  1587.1  962.44  1813.4  944.56
#Mann= 3 , 0 , 0
       0      .1       0   304.5    .045       0   402.7      .1       0
Bank Sta=304.5,402.7
XS Rating Curve= 0 ,0
Exp/Cntr=0.3,0.1

Type RM Length L Ch R = 1 ,30695.2 ,509.3,502.8,496.2
XS GIS Cut Line= 4
     1749253.013      446745.399     1749825.019      447262.928
     1749957.529      447764.506     1750607.529        447979.1
#Sta/Elev= 30
       0  787.05    78.1  746.58   224.6   656.6   244.1  641.53   273.4   626.9
   292.9  621.75     315  610.77     332   608.9   400.3  608.92     415   610.8
   439.4  619.74   468.7  619.48   517.5  630.48   615.2     635   683.5  641.97
   712.8  655.84   742.1  663.31   839.9   716.3   957.4  783.42   996.5  803.36
  1055.2  829.43  1182.5   872.2  1290.2  896.15  1378.2  902.66  1515.1  890.93
  1583.5  888.04  1710.6  894.85  1798.7  895.45    1916  905.31  1974.7  904.86
#Mann= 3 , 0 , 0
       0      .1       0     315    .045       0     415      .1       0
Bank Sta=315,415
XS Rating Curve= 0 ,0
Exp/Cntr=0.3,0.1

Type RM Length L Ch R = 1 ,30192.5 ,441.4,444.6,447.6
XS GIS Cut Line= 2
     1748870.404      447131.519     1749606.094       447672.76
#Sta/Elev= 30
       0  723.53    39.3  712.79    98.2  701.39   117.8  696.47     167  679.51
   196.4  670.36   235.7   659.2   255.3  651.99   294.6  635.39   324.1   625.2
   333.9  621.01   353.6  611.14   363.4  609.06   373.2   608.9   441.9  608.91
   451.8  609.16   461.6  610.68   481.2  617.39     491  619.71   540.1  627.46
   559.8  628.97   599.1  629.71   628.5  631.22   726.7   640.4   746.4  647.43
     766  651.69     825  686.14   854.4  704.33   883.9  724.18   913.3  745.78
#Mann= 3 , 0 , 0
       0      .1       0   353.6    .045       0   461.6      .1       0
Bank Sta=353.6,461.6
XS Rating Curve= 0 ,0
Exp/Cntr=0.3,0.1

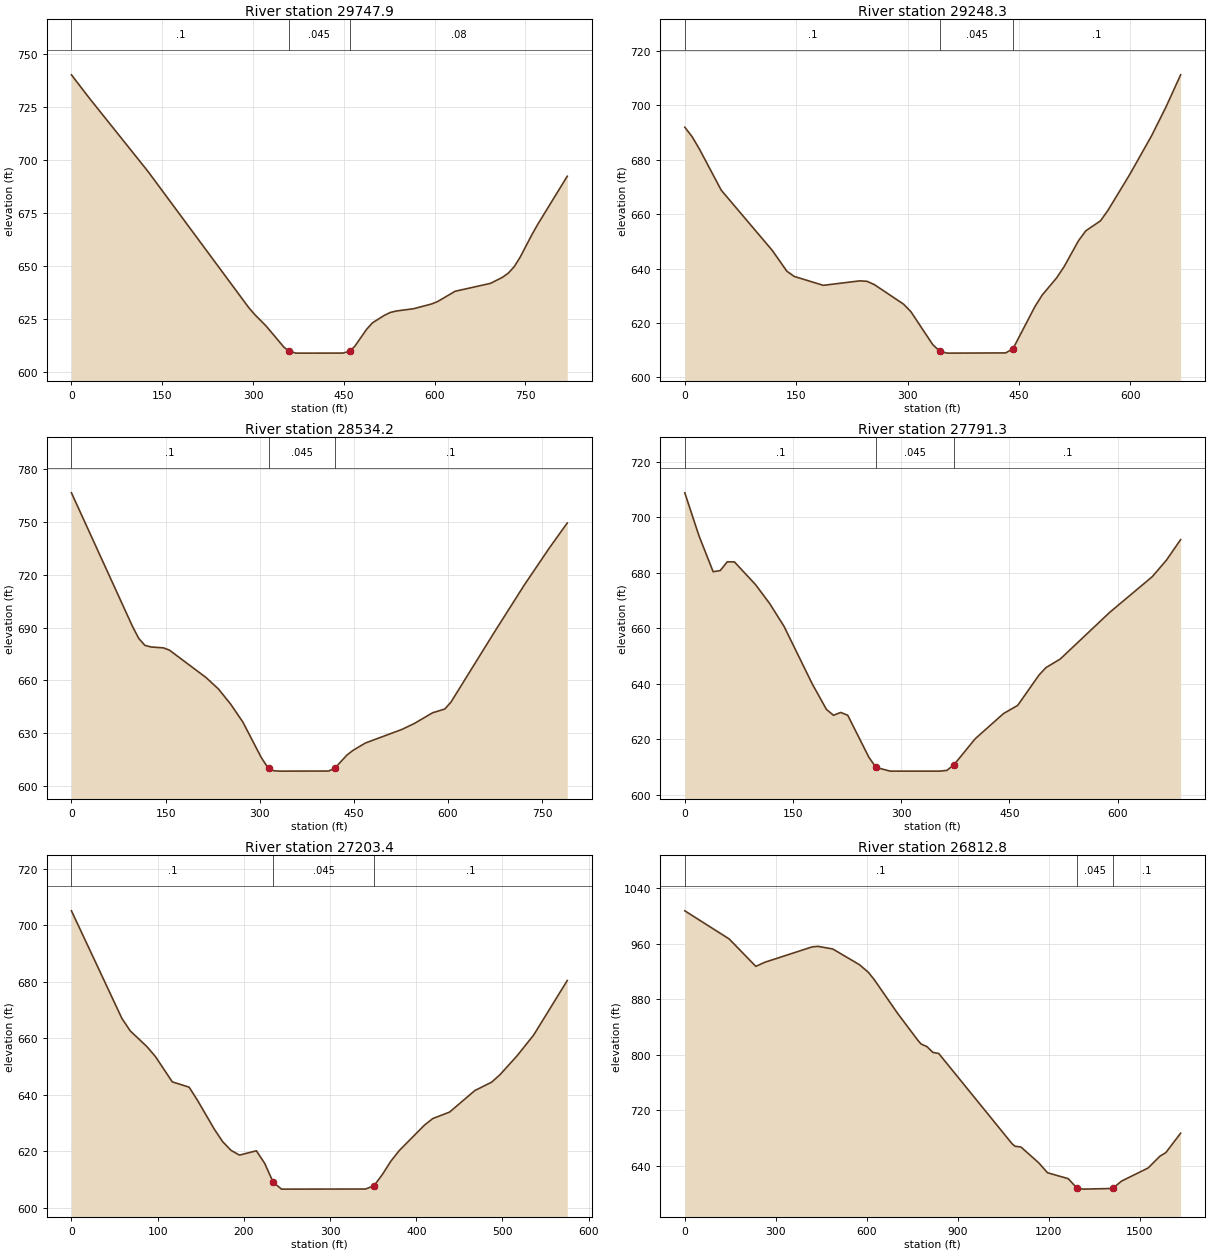
Type RM Length L Ch R = 1 ,29747.9 ,461.5,499.6,537.9
XS GIS Cut Line= 3
     1748619.293      447473.615     1748937.005      447731.976
     1749255.286      447989.632
#Sta/Elev= 30
       0  740.04    29.2  729.18   126.8  694.38   292.5  630.49   302.2  627.24
   321.8   621.6     351   611.7   359.5  609.83   370.5  608.91   380.2   608.9
   448.5  608.92   459.5  609.78     468  612.11   487.5   620.1   497.2  623.18
   516.8  626.69   526.5  628.05   536.2  628.72   565.5  629.85   594.8  632.05
   604.5  633.16   633.8  638.05   692.2  641.78   711.8   644.6   721.5  646.57
   731.2  649.58     741  654.02   760.5  664.68   770.2  669.57     819  692.25
#Mann= 3 , 0 , 0
       0      .1       0   359.5    .045       0   459.5     .08       0
Bank Sta=359.5,459.5
XS Rating Curve= 0 ,0
Exp/Cntr=0.3,0.1

Type RM Length L Ch R = 1 ,29248.3 ,721.1,714.1,707.1
XS GIS Cut Line= 2
     1748458.486       447688.31     1748657.529       448325.87
#Sta/Elev= 30
       0  691.98     9.8  688.52    19.6  683.99    49.1  668.82   117.9  646.65
   137.5  639.02   147.3  637.12   186.6  633.83   235.7  635.48   245.6   635.3
   255.4  634.09   294.7  626.91   304.5  624.17     334  612.03   343.8  609.52
   353.6   608.9   432.2  608.98     442  610.48   471.5  625.95   481.3  630.21
   500.9  636.59   510.8  640.63   530.4  650.27   540.2  653.89   559.9  657.54
   569.7  661.28   599.2  674.53   628.6  688.75   648.3   699.5   667.9  711.25
#Mann= 3 , 0 , 0
       0      .1       0   343.8    .045       0     442      .1       0
Bank Sta=343.8,442
XS Rating Curve= 0 ,0
Exp/Cntr=0.3,0.1

Type RM Length L Ch R = 1 ,28534.2 ,744.7,742.9,741.2
XS GIS Cut Line= 2
     1747737.266      447888.456     1748051.745      448613.197
#Sta/Elev= 30
       0  766.34    97.5  690.45   107.3  683.79     117   679.9   126.8  678.96
   146.3  678.48   156.1  677.19   214.6   661.6   234.1   655.2   253.6  646.61
   273.1  636.42   302.4  616.33   312.1  611.03   314.3  610.53   321.9  608.82
   331.6   608.6   409.6  608.65   419.4  610.16   438.9   617.7   448.7  620.38
   468.2  624.52   526.7  632.26   546.2  635.58   575.4  641.66     595  643.83
   604.7  647.72     673  686.89   721.8  714.24   760.8  734.74     790  749.26
#Mann= 3 , 0 , 0
       0      .1       0   314.3    .045       0   419.4      .1       0
Bank Sta=314.3,419.4
XS Rating Curve= 0 ,0
Exp/Cntr=0.3,0.1

Type RM Length L Ch R = 1 ,27791.3 ,589,587.9,586.7
XS GIS Cut Line= 2
     1747128.099      448339.606     1747418.942      448962.513
#Sta/Elev= 30
       0  708.85    19.6  693.41    39.3  680.43    49.1  680.84    58.9  684.01
    68.8  683.97    98.2  675.75   117.8  668.92   137.5   660.8   176.8  639.98
   196.4  630.83   206.2  628.71   216.1  629.74   225.9  628.73   255.3  613.57
   265.2  609.93   284.8   608.6   353.6   608.6   363.4  608.87   373.2  610.89
   402.7  620.27   441.9  629.34   461.6  632.28     491  643.17   500.9  645.92
   520.5  648.96   589.2   665.8   648.2  678.65   667.8  684.59   687.5     692
#Mann= 3 , 0 , 0
       0      .1       0   265.2    .045       0   373.2      .1       0
Bank Sta=265.2,373.2
XS Rating Curve= 0 ,0
Exp/Cntr=0.3,0.1

Type RM Length L Ch R = 1 ,27203.4 ,388.1,390.6,393.1
XS GIS Cut Line= 2
     1746614.972      448640.649      1746867.75      449157.316
#Sta/Elev= 30
       0  705.19    58.5   667.1    68.2  662.66    87.7  657.04    97.5  653.53
     117   644.6   136.5  642.72   146.2  638.08   165.7  627.86   175.5  623.38
   185.2  620.32     195  618.65   214.5  620.19   224.2  615.72     234  609.04
   243.7   606.6   341.2  606.64     351  607.79   360.7  611.78   370.5  616.48
   380.2  620.22   409.5  629.27   419.2   631.6   438.7   633.9     468  641.53
   487.4  644.48   497.2  647.16   516.7  653.73   536.2  661.18   575.2   680.5
#Mann= 3 , 0 , 0
       0      .1       0     234    .045       0     351      .1       0
Bank Sta=234,351
XS Rating Curve= 0 ,0
Exp/Cntr=0.3,0.1

Type RM Length L Ch R = 1 ,26812.8 ,450.1,484.3,524.3
XS GIS Cut Line= 4
     1746184.307      447781.392     1746385.928      448372.532
     1746296.849       448857.89     1746506.289      449330.626
#Sta/Elev= 30
       0 1007.62   146.4  967.04   234.2  927.52   263.5  933.41   419.6  955.57
   439.2  956.41     488   952.6   575.8  929.97   605.1  919.07   624.6  908.49
     702  859.62   769.7  820.29   779.4  815.53   798.7  811.76   818.1   803.5
   837.4  801.93  1079.3  671.72    1089  668.13  1108.4  667.07  1166.8  644.41
  1196.1  629.92  1264.4  621.41  1293.6  607.58  1313.2   606.3  1410.7  607.22
    1440  617.81  1527.8  636.77  1566.8  653.81  1586.3  658.94  1635.1  686.96
#Mann= 3 , 0 , 0
       0      .1       0  1293.6    .045       0  1410.7      .1       0
Bank Sta=1293.6,1410.7
XS Rating Curve= 0 ,0
Exp/Cntr=0.3,0.1

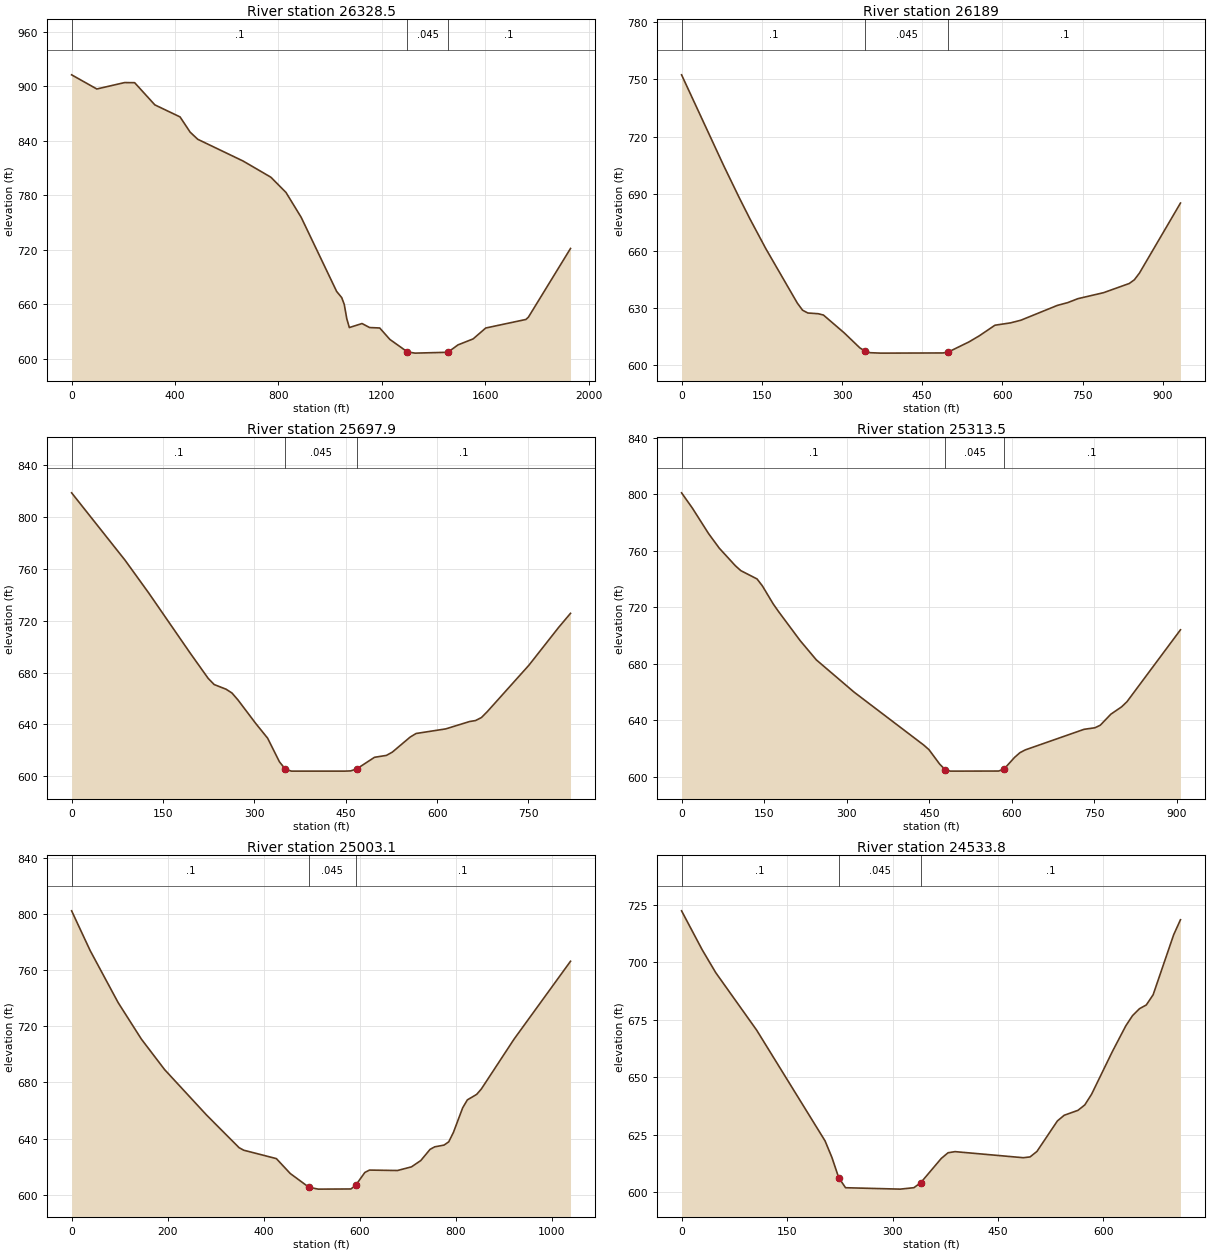
Type RM Length L Ch R = 1 ,26328.5 ,124.3,139.5,165.1
XS GIS Cut Line= 5
      1744960.01       448606.59     1745687.781      449043.001
     1745983.453      449113.667     1745971.274      449679.637
     1746110.473      449837.979
#Sta/Elev= 30
       0  912.59    97.5     897   204.8  904.06   243.8  903.93   321.9  879.51
   419.4  866.26   458.4  849.49   487.7  841.64   663.3  817.67   770.6  799.88
   829.1   783.1   887.8  755.75  1025.1  674.07  1044.7   667.3  1054.5  659.78
  1064.3     644  1074.1  634.35  1123.2  638.78  1152.6  634.35  1191.6  633.89
  1230.7  621.33    1299  607.49  1328.3   606.2  1455.2  607.13  1494.2  615.25
  1552.8  621.84  1601.6  633.85    1757  643.27  1766.6  645.77  1929.5  721.42
#Mann= 3 , 0 , 0
       0      .1       0    1299    .045       0  1455.2      .1       0
Bank Sta=1299,1455.2
XS Rating Curve= 0 ,0
Exp/Cntr=0.3,0.1

Type RM Length L Ch R = 1 ,26189   ,590.9,491.1,374.9
XS GIS Cut Line= 4
     1745672.278      449141.798     1745885.198      449243.913
     1745874.746      449729.637     1746013.945      449887.979
#Sta/Elev= 30
       0  752.44    78.7  704.76   108.2  687.66   127.9   676.7   157.4  661.16
   216.5  632.46   226.3  628.75   236.1  627.29   255.6   626.9   265.3  626.21
   304.2  616.82   333.3  608.97     343  607.28   352.7  606.42   372.2   606.2
   488.8  606.29   498.5  606.76   537.4   612.1   556.8  615.32   585.9  620.86
   615.1   622.1   634.5   623.5   702.5  631.27     722  632.74   741.1  634.82
   789.1  637.97     837  642.79   846.6  644.74   856.1  648.26   932.8  685.06
#Mann= 3 , 0 , 0
       0      .1       0     343    .045       0   498.5      .1       0
Bank Sta=343,498.5
XS Rating Curve= 0 ,0
Exp/Cntr=0.3,0.1

Type RM Length L Ch R = 1 ,25697.9 ,395.4,384.4,373.4
XS GIS Cut Line= 3
     1745288.502       449714.24     1745669.115      449865.318
     1746049.727      450016.396
#Sta/Elev= 30
       0  818.37    87.8  766.45   126.8  741.12     195  694.75   224.2  675.52
     234  670.77   253.5  667.19   263.2  664.26     273  658.97   302.2  640.84
   321.8  629.46   341.2  611.27     351  605.54   360.8   604.1   448.5   604.1
   458.2  604.28     468  605.79   497.2  614.74   516.8  616.21   526.5  618.73
   555.8  630.33   565.5  633.07   614.2  636.62   653.2  642.27     663  643.03
   672.8  645.36   682.5  649.96   750.8  685.69   799.5  714.75     819  725.59
#Mann= 3 , 0 , 0
       0      .1       0     351    .045       0     468      .1       0
Bank Sta=351,468
XS Rating Curve= 0 ,0
Exp/Cntr=0.3,0.1

Type RM Length L Ch R = 1 ,25313.5 ,310.4,310.4,310.4
XS GIS Cut Line= 3
     1745139.747      449972.653     1745363.567      450191.942
     1745943.567      450314.667
#Sta/Elev= 30
       0  800.95    19.6  790.16      49  772.15    68.5   761.8    97.9   749.3
   107.7   745.9   137.1  740.03   146.9  735.06   166.5  722.34   176.2  716.95
   215.4  696.41   244.8  682.79   313.3     660   439.7  622.59   449.4  619.28
   468.8  609.08   478.6   605.2   488.3   604.1   575.8  604.16   585.5  605.49
   604.9  613.83   614.6  617.14   624.3  619.12   731.2  633.69   750.7  634.76
   760.4  636.53   779.8  644.39   799.3  649.57     809  653.19   906.2  704.06
#Mann= 3 , 0 , 0
       0      .1       0   478.6    .045       0   585.5      .1       0
Bank Sta=478.6,585.5
XS Rating Curve= 0 ,0
Exp/Cntr=0.3,0.1

Type RM Length L Ch R = 1 ,25003.1 ,477.6,469.3,460.9
XS GIS Cut Line= 4
      1745004.33      450564.667     1745275.164      450490.014
     1745882.803      450618.487      1745995.65      450696.612
#Sta/Elev= 30
       0  802.08    38.8   773.7    96.9  736.81   145.3  710.84   193.8   689.1
   280.9  656.89   348.9  633.57   358.6  631.78   426.5  625.82   455.6  615.17
   494.4  605.42   513.8   604.1   581.8  604.21   591.5  606.72   610.9  615.97
   620.6  617.65   678.8  617.34   707.9  619.93   727.3   624.4   746.7  632.37
   756.4  634.18   775.8  635.42   785.6  637.75   795.3  644.38   814.7  661.98
   824.4  667.58   843.8   671.5   853.5  675.32   921.6  710.76  1039.3   766.2
#Mann= 3 , 0 , 0
       0      .1       0   494.4    .045       0   591.5      .1       0
Bank Sta=494.4,591.5
XS Rating Curve= 0 ,0
Exp/Cntr=0.3,0.1

Type RM Length L Ch R = 1 ,24533.8 ,665.5,635.9,608.3
XS GIS Cut Line= 2
     1745139.893       450978.99     1745847.079      451035.826
#Sta/Elev= 30
       0  722.31    29.2  705.46    48.6  695.45   106.9  670.42   204.1  622.34
   213.8  615.19   223.5  606.38   233.2  602.01     311   601.4   330.4  602.02
   340.2  604.22   369.3  614.72     379   617.2   388.8  617.69   485.9  615.05
   495.6  615.39   505.4  617.78   534.5  631.04   544.2   633.5   563.7  635.63
   573.4  637.97   583.1  642.63   612.3  660.96   631.7  672.32   641.4  676.81
   651.2  679.78   660.9  681.42   670.6  685.83   699.8  711.89   709.5  718.43
#Mann= 3 , 0 , 0
       0      .1       0   223.5    .045       0   340.2      .1       0
Bank Sta=223.5,340.2
XS Rating Curve= 0 ,0
Exp/Cntr=0.3,0.1

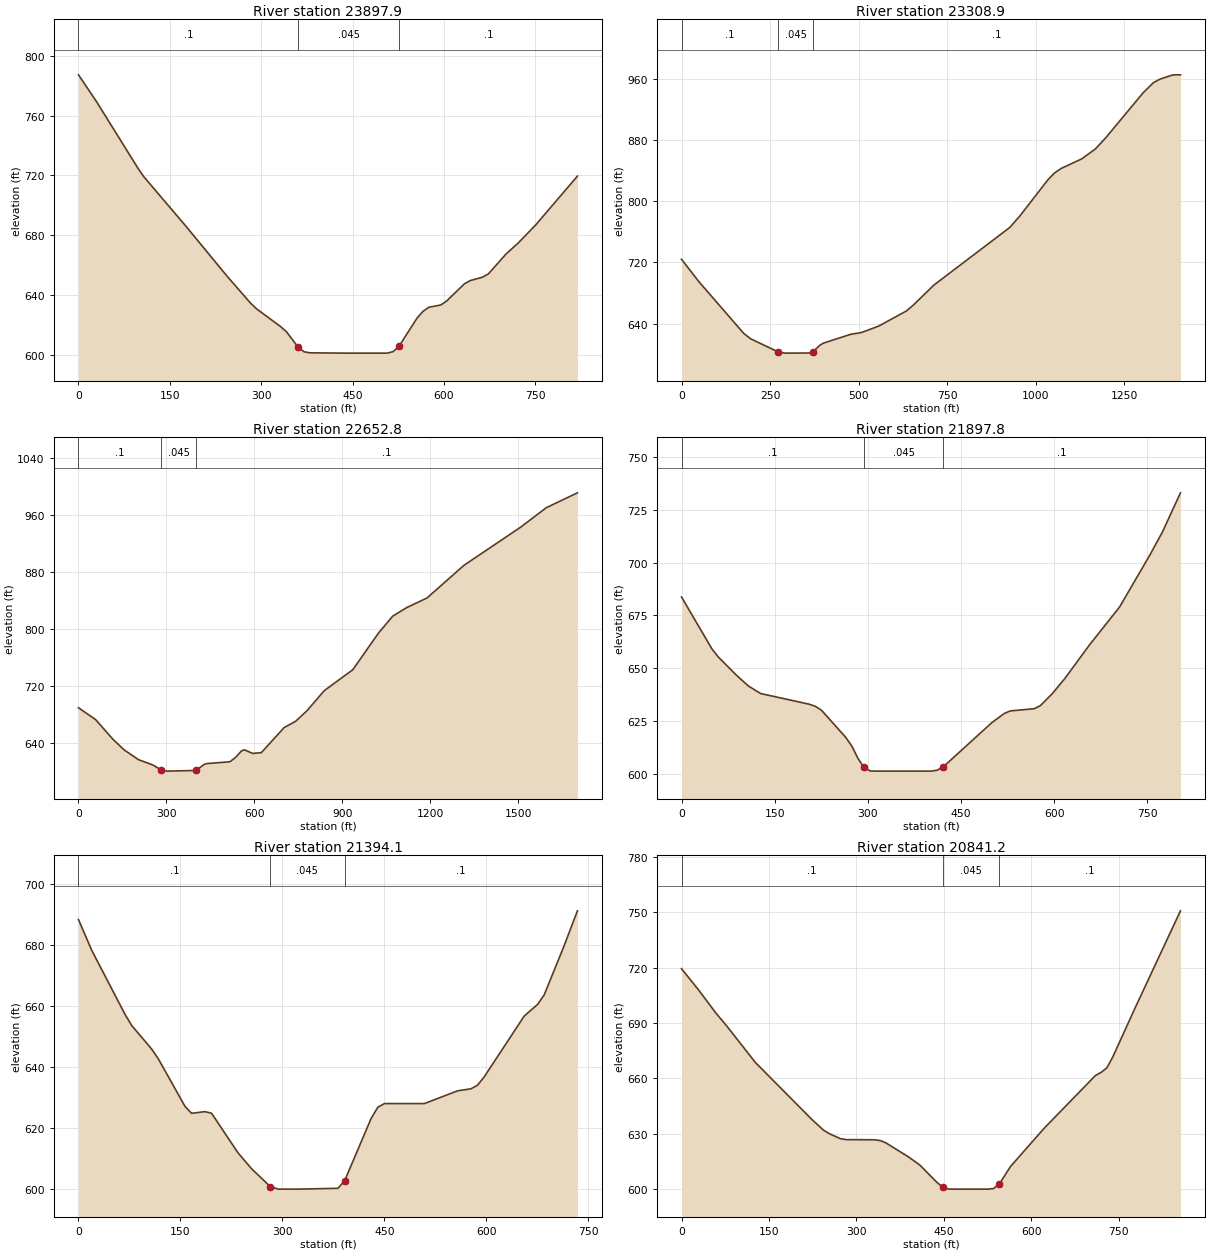
Type RM Length L Ch R = 1 ,23897.9 ,592.3,589,583.8
XS GIS Cut Line= 3
     1745172.509      451775.313     1745553.461      451625.205
     1745939.088      451486.737
#Sta/Elev= 30
       0  787.32    29.2  769.65    97.5  724.95   107.2  719.21   175.5  686.52
   243.7  652.78   282.7  634.55   292.5  630.78   331.5  619.05   341.2  615.62
   360.7  605.14   370.5  602.08   380.2   601.4   438.7   601.2     507   601.2
   516.8  602.24   526.5  605.94   555.8  624.58   565.6  629.15   575.3   631.9
   594.8  633.38   604.6  636.12   633.8  647.61   643.6  649.78   663.1  651.94
   672.9  654.15   702.1  667.55   721.6  674.69   750.9  687.04   819.2   719.6
#Mann= 3 , 0 , 0
       0      .1       0   360.7    .045       0   526.5      .1       0
Bank Sta=360.7,526.5
XS Rating Curve= 0 ,0
Exp/Cntr=0.3,0.1

Type RM Length L Ch R = 1 ,23308.9 ,639.9,656.1,672.1
XS GIS Cut Line= 4
     1745493.439      452298.256      1746072.05      452036.543
     1746358.731       451758.94     1746567.976      451448.025
#Sta/Elev= 30
       0  724.15    48.8  695.01   175.9  626.94   195.4  619.94   273.6  602.68
   293.1   601.2   361.5  601.35   371.3  602.96   390.8   611.6   400.6  614.31
   478.7     626     508  628.16   556.9  636.64     635  656.44   654.5  664.14
   712.9  690.45     927  765.88   956.2  781.38  1034.1  828.03  1053.3  837.27
  1072.6  843.32  1130.2  855.73  1168.6  868.72  1197.5  883.13  1303.2  942.18
    1332  955.35  1351.2  960.23    1380  964.66  1389.7  965.85  1408.9  965.83
#Mann= 3 , 0 , 0
       0      .1       0   273.6    .045       0   371.3      .1       0
Bank Sta=273.6,371.3
XS Rating Curve= 0 ,0
Exp/Cntr=0.3,0.1

Type RM Length L Ch R = 1 ,22652.8 ,701.2,755,808.5
XS GIS Cut Line= 4
     1745673.994       452836.45     1746403.161      452706.242
     1746703.508      453126.381     1746877.119      453536.103
#Sta/Elev= 30
       0  690.03    58.5  673.38     117   646.1   155.9  630.92   204.7  617.27
   253.4  609.86   282.6  602.78   302.1   601.2   401.1  602.11   428.8  610.67
   438.6  611.78   516.5  614.31     536  620.49   555.5  629.23   565.3  631.16
   594.5  626.01   623.8  627.12   701.7   662.3   740.7  671.03   779.7  685.92
   838.2   713.9   935.6  743.23  1023.3  794.61    1072   818.4  1120.7  830.62
  1188.9  843.84  1315.2  889.68  1508.7  943.17  1595.7  970.32  1702.1  991.21
#Mann= 3 , 0 , 0
       0      .1       0   282.6    .045       0   401.1      .1       0
Bank Sta=282.6,401.1
XS Rating Curve= 0 ,0
Exp/Cntr=0.3,0.1

Type RM Length L Ch R = 1 ,21897.8 ,478.8,503.7,528.6
XS GIS Cut Line= 2
     1745460.794      453222.787     1746101.419      453707.162
#Sta/Elev= 30
       0  683.74      49  659.14    58.8  655.43    88.2  646.72   107.7  641.54
   127.3  637.99   205.7  632.91   215.5  631.92   225.3  630.07   264.4  617.19
   274.2  613.06     284  607.24   293.8  602.92   303.6   601.3   313.4   601.2
   401.6  601.21   411.4   601.6   421.2   603.2   499.5  624.19   519.1  628.44
   528.9  629.72   568.1  630.81   577.9  632.31   597.4  638.13     617  645.11
   656.2  660.85   705.2  679.05   754.2  703.84   773.8  714.39   803.1  733.12
#Mann= 3 , 0 , 0
       0      .1       0   293.8    .045       0   421.2      .1       0
Bank Sta=293.8,421.2
XS Rating Curve= 0 ,0
Exp/Cntr=0.3,0.1

Type RM Length L Ch R = 1 ,21394.1 ,508.6,552.9,597.2
XS GIS Cut Line= 2
     1745211.147       453490.27     1745588.925      454119.437
#Sta/Elev= 30
       0  688.35    19.6  678.22    68.5   657.3    78.3  653.67   107.6  645.97
   117.4  642.78   156.6  627.23   166.3  624.93   185.9  625.48   195.7  624.96
   234.8  611.95   254.4  606.84     282  600.97   293.6  600.13   322.9  600.12
   381.6  600.39   391.4  602.83   430.5  623.27   440.3  626.94   450.1  628.12
   508.8  628.12   557.7   632.3   577.3  632.95   587.1  634.16   596.9  636.91
   655.6  656.75   675.2  660.55     685  663.69   714.3  679.75   733.9   691.2
#Mann= 3 , 0 , 0
       0      .1       0     282    .045       0   391.4      .1       0
Bank Sta=282,391.4
XS Rating Curve= 0 ,0
Exp/Cntr=0.3,0.1

Type RM Length L Ch R = 1 ,20841.2 ,820.9,861.6,902.4
XS GIS Cut Line= 3
     1744965.314       453490.27     1744901.425      453805.548
     1744827.814      454334.714
#Sta/Elev= 30
       0  719.47    29.2  707.97    58.5  695.63      78  688.23   126.7  668.61
   224.2  637.52   243.7  631.86   253.4  629.99     273  627.24   282.7  626.74
   331.4  626.66   341.1  626.22   350.8  624.96   389.7  617.32   409.1  612.89
   438.2  603.56     448     601   457.7  599.96   467.4   599.9   525.7   599.9
   535.4  600.25   545.1  602.63   564.5   612.2   622.8  633.14   710.2  661.54
     720  663.26   729.7  665.69   739.4  671.26   778.2   698.2     856  750.85
#Mann= 3 , 0 , 0
       0      .1       0     448    .045       0   545.1      .1       0
Bank Sta=448,545.1
XS Rating Curve= 0 ,0
Exp/Cntr=0.3,0.1

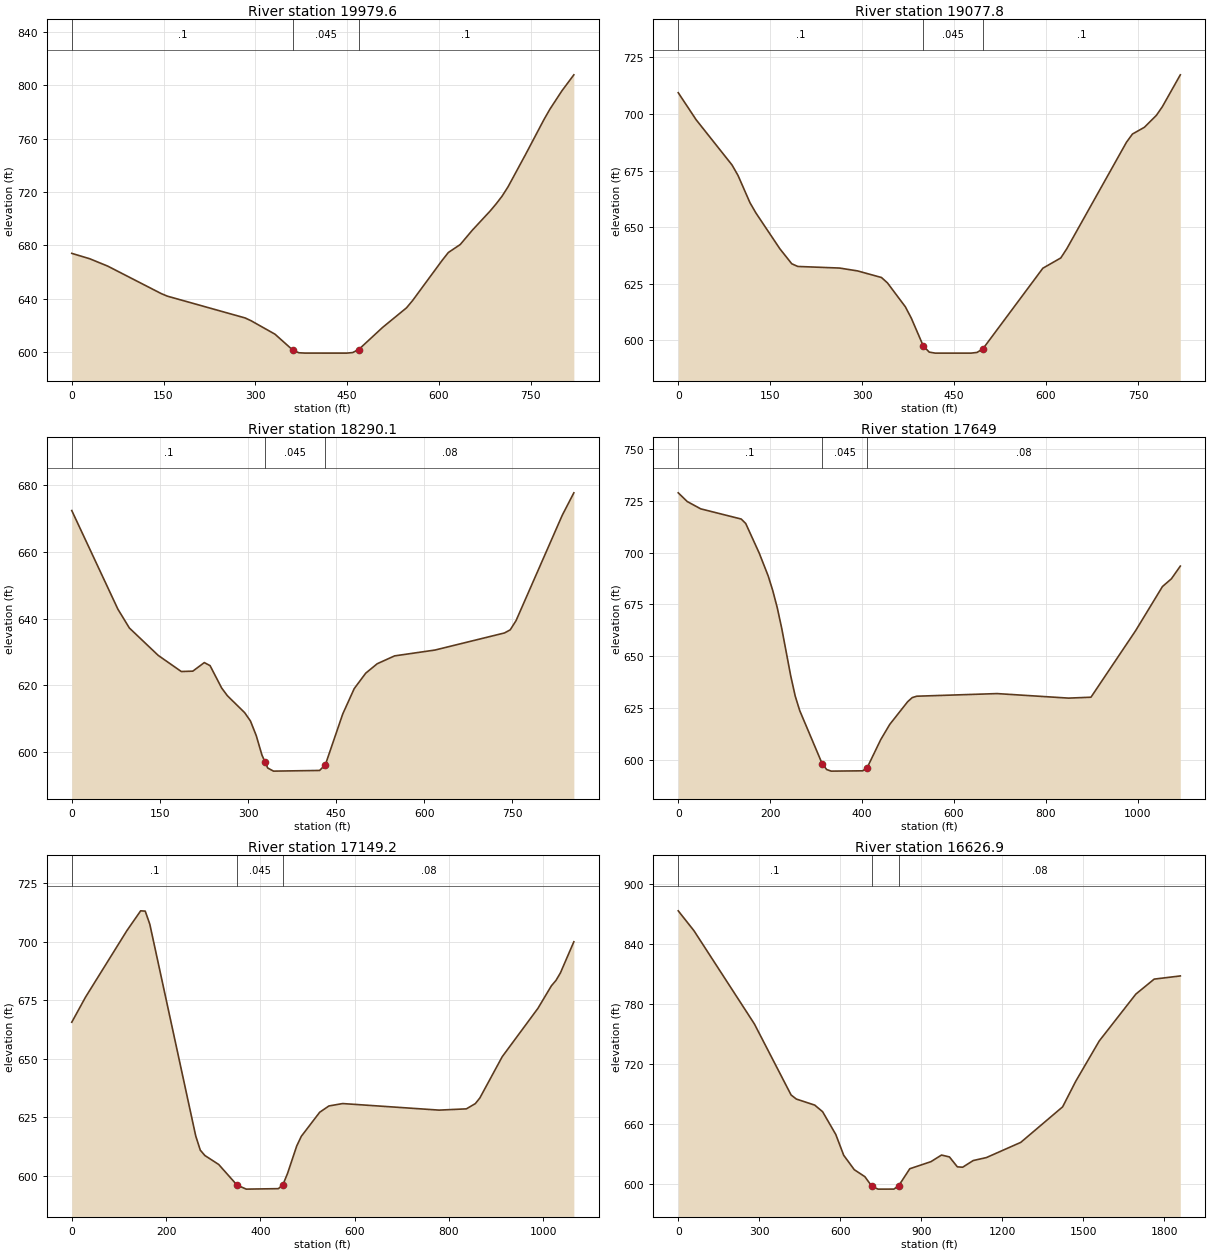
Type RM Length L Ch R = 1 ,19979.6 ,900.2,901.8,903.5
XS GIS Cut Line= 2
     1744433.041      453245.136     1743865.314      453837.492
#Sta/Elev= 30
       0  674.04    29.3  670.01    58.6  664.52   146.5  643.84   156.3  641.97
   283.3  625.66     293  623.58   332.1   613.5   361.4   601.5   371.2  599.58
   380.9  599.33   449.3  599.31   459.1  599.74   468.8  601.96   507.9  618.54
     547  633.22   556.8  638.58   605.6  668.99   615.4  674.67   634.9  680.68
   654.4  691.29   683.7  705.75   693.5   711.1   703.3  716.93     713  723.91
   742.4   748.8   771.6  774.21   781.4  782.05     801  795.79   820.5  807.77
#Mann= 3 , 0 , 0
       0      .1       0   361.4    .045       0   468.8      .1       0
Bank Sta=361.4,468.8
XS Rating Curve= 0 ,0
Exp/Cntr=0.3,0.1

Type RM Length L Ch R = 1 ,19077.8 ,790.6,787.6,784.7
XS GIS Cut Line= 3
     1743878.207      452545.101     1743587.322      452833.331
     1743296.438       453121.56
#Sta/Elev= 30
       0  709.44    29.2   697.5    87.8   677.5    97.5  672.91     117  660.86
   126.8  656.28   165.8  640.49   185.2  633.87     195  632.69   263.2  631.98
   292.5  630.72   331.5  627.81   341.2  625.46   370.5  614.86   380.2  609.85
   399.8  597.53   409.5  594.84   419.2   594.4   477.8   594.4   487.5  594.71
   497.2  596.38   594.8  631.91     624  636.44   633.8   640.5   731.2  687.57
     741   691.2   760.5  694.18     780  699.45   789.8   703.3     819  717.34
#Mann= 3 , 0 , 0
       0      .1       0   399.8    .045       0   497.2      .1       0
Bank Sta=399.8,497.2
XS Rating Curve= 0 ,0
Exp/Cntr=0.3,0.1

Type RM Length L Ch R = 1 ,18290.1 ,688.8,641.1,593.4
XS GIS Cut Line= 3
     1743213.532      452075.576     1742861.141      452457.856
     1742697.252      452749.523
#Sta/Elev= 30
       0  672.25    78.5  642.79    98.1  637.15   147.2  628.97   186.4  624.16
     206  624.27   225.6  626.83   235.4  625.91   255.1  619.23   264.9  616.92
   294.3  611.86   304.1  609.38   313.9  605.05   323.7  599.19   329.2  597.02
   333.5  595.33   343.3   594.4   421.8   594.6   431.6  596.31   461.1  611.44
   480.7  619.05   500.3  623.67   519.9  626.49   549.4  628.83   618.3  630.58
   736.4  635.68   746.2  636.61   756.1  639.35   834.8  670.86   854.5  677.55
#Mann= 3 , 0 , 0
       0      .1       0   329.2    .045       0   431.6     .08       0
Bank Sta=329.2,431.6
XS Rating Curve= 0 ,0
Exp/Cntr=0.3,0.1

Type RM Length L Ch R = 1 ,17649   ,517,499.9,482.6
XS GIS Cut Line= 3
     1742418.511      451680.114     1742411.567      452199.211
      1742378.58      452772.128
#Sta/Elev= 30
       0     729    19.6  724.79      49  721.25   137.1  716.32   146.9  714.18
   176.3  699.86   195.9  688.76   205.7  681.79   215.5   673.5   225.3  663.46
   244.9  640.45   254.7  630.68   264.5  623.66   313.4  597.96   323.2  595.16
     333   594.4   401.6  594.55   411.4  596.11   440.8  609.62   460.4  616.98
   499.6  628.02   509.4  629.95   519.1  630.63   694.2   631.9   849.8  629.71
   898.5  630.15   995.7  662.33  1054.1  683.67  1073.6  687.42    1093  693.56
#Mann= 3 , 0 , 0
       0      .1       0   313.4    .045       0   411.4     .08       0
Bank Sta=313.4,411.4
XS Rating Curve= 0 ,0
Exp/Cntr=0.3,0.1

Type RM Length L Ch R = 1 ,17149.2 ,538.3,522.3,506.3
XS GIS Cut Line= 3
     1741830.699      451781.792     1742033.404      452574.187
     1742059.216      452819.731
#Sta/Elev= 30
       0  665.65    29.2  676.37   116.8  704.72   146.1  713.21   155.8  713.08
   165.5  707.51   262.9  617.09   272.6  611.03   282.4  608.74   311.6  604.93
   350.5  596.12     370   594.4   438.2   594.6   447.9  596.32   457.6   601.1
   477.1  612.83   486.8  616.94   525.8  627.22   545.3   629.9   574.5  630.93
     779  628.13   836.9  628.67   855.9  630.91   865.4   633.3   912.9  650.93
   988.8  671.63  1017.3  681.23  1026.8  683.47  1036.3   686.7  1064.8     700
#Mann= 3 , 0 , 0
       0      .1       0   350.5    .045       0   447.9     .08       0
Bank Sta=350.5,447.9
XS Rating Curve= 0 ,0
Exp/Cntr=0.3,0.1

Type RM Length L Ch R = 1 ,16626.9 ,594,553.9,513.7
XS GIS Cut Line= 4
     1740986.219       451721.78     1741335.178      452152.336
     1741675.455      452780.808     1742109.483       453181.85
#Sta/Elev= 30
       0  873.22    58.3  853.28     282  759.95   418.1  688.72   437.5  684.64
   505.6  678.58   534.8  671.97   583.6  649.17     613  628.31   652.1  613.88
   691.3  606.89   717.1  597.27   740.2   594.4     799  594.43   817.1     598
   857.7  614.81     936  621.91   975.2  628.54  1004.6  626.66  1033.9  616.74
  1053.5  616.35  1092.7  623.04  1141.6  626.02  1268.9  641.25  1423.9  676.85
  1472.3  702.38  1559.5  742.83  1695.1   789.8    1763   804.8  1859.8  807.99
#Mann= 3 , 0 , 0
       0      .1       0   717.1    .045       0   817.1     .08       0
Bank Sta=717.1,817.1
XS Rating Curve= 0 ,0
Exp/Cntr=0.3,0.1