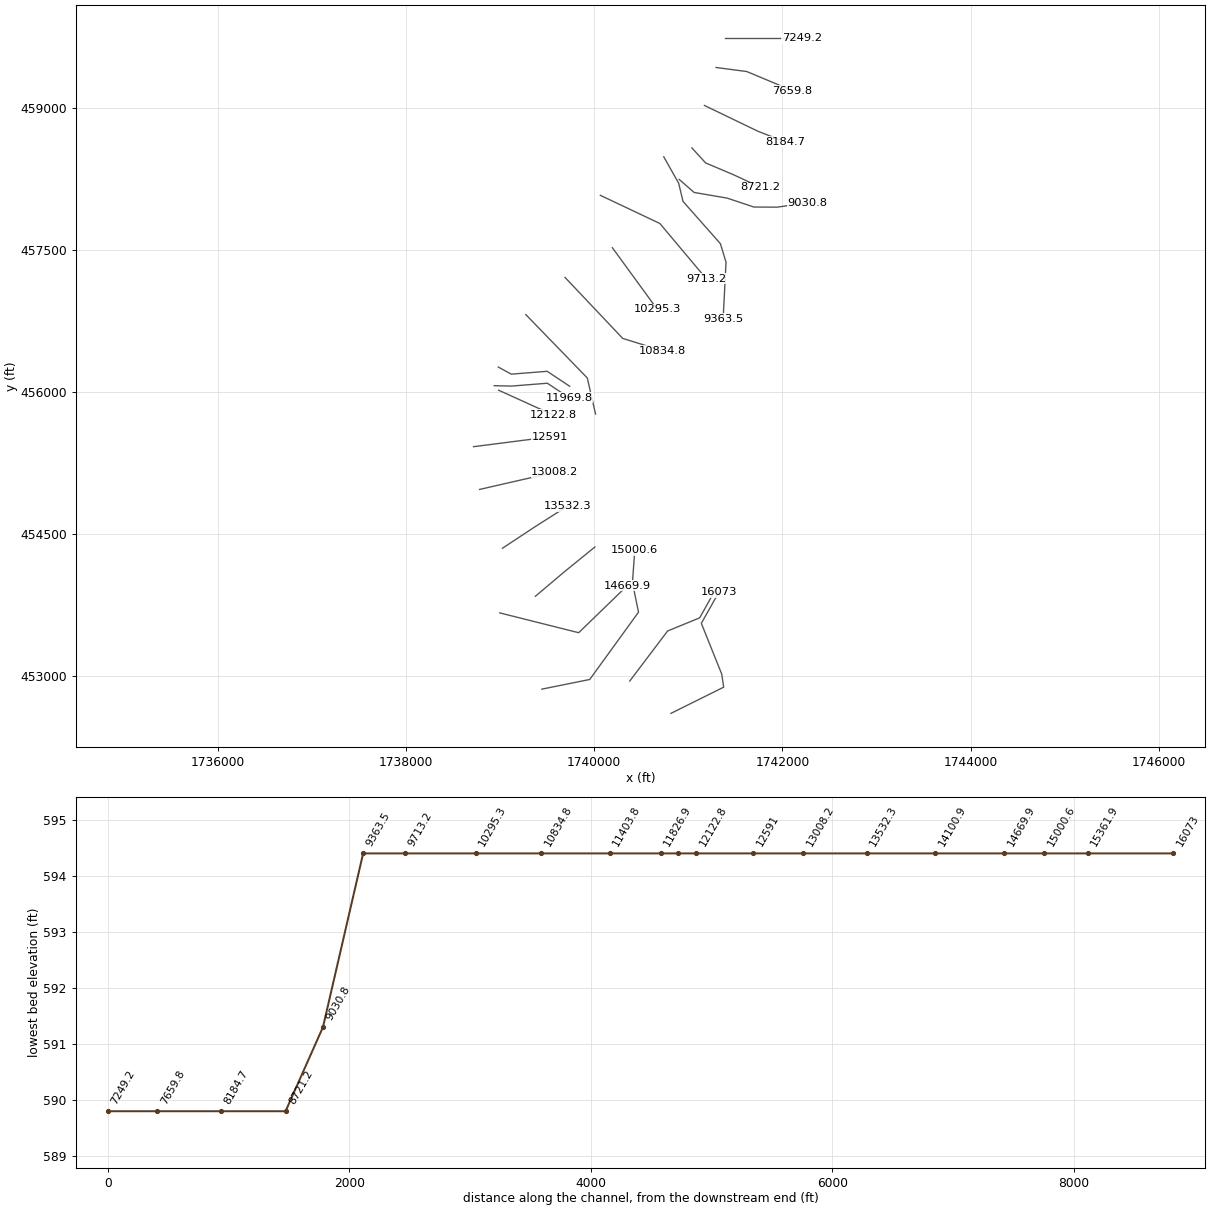
HEC-RAS study BIGCOALRIV.prj: BIGCOALRIV

--- BIGCOALRIV.g01 (geometry) --- (continued)

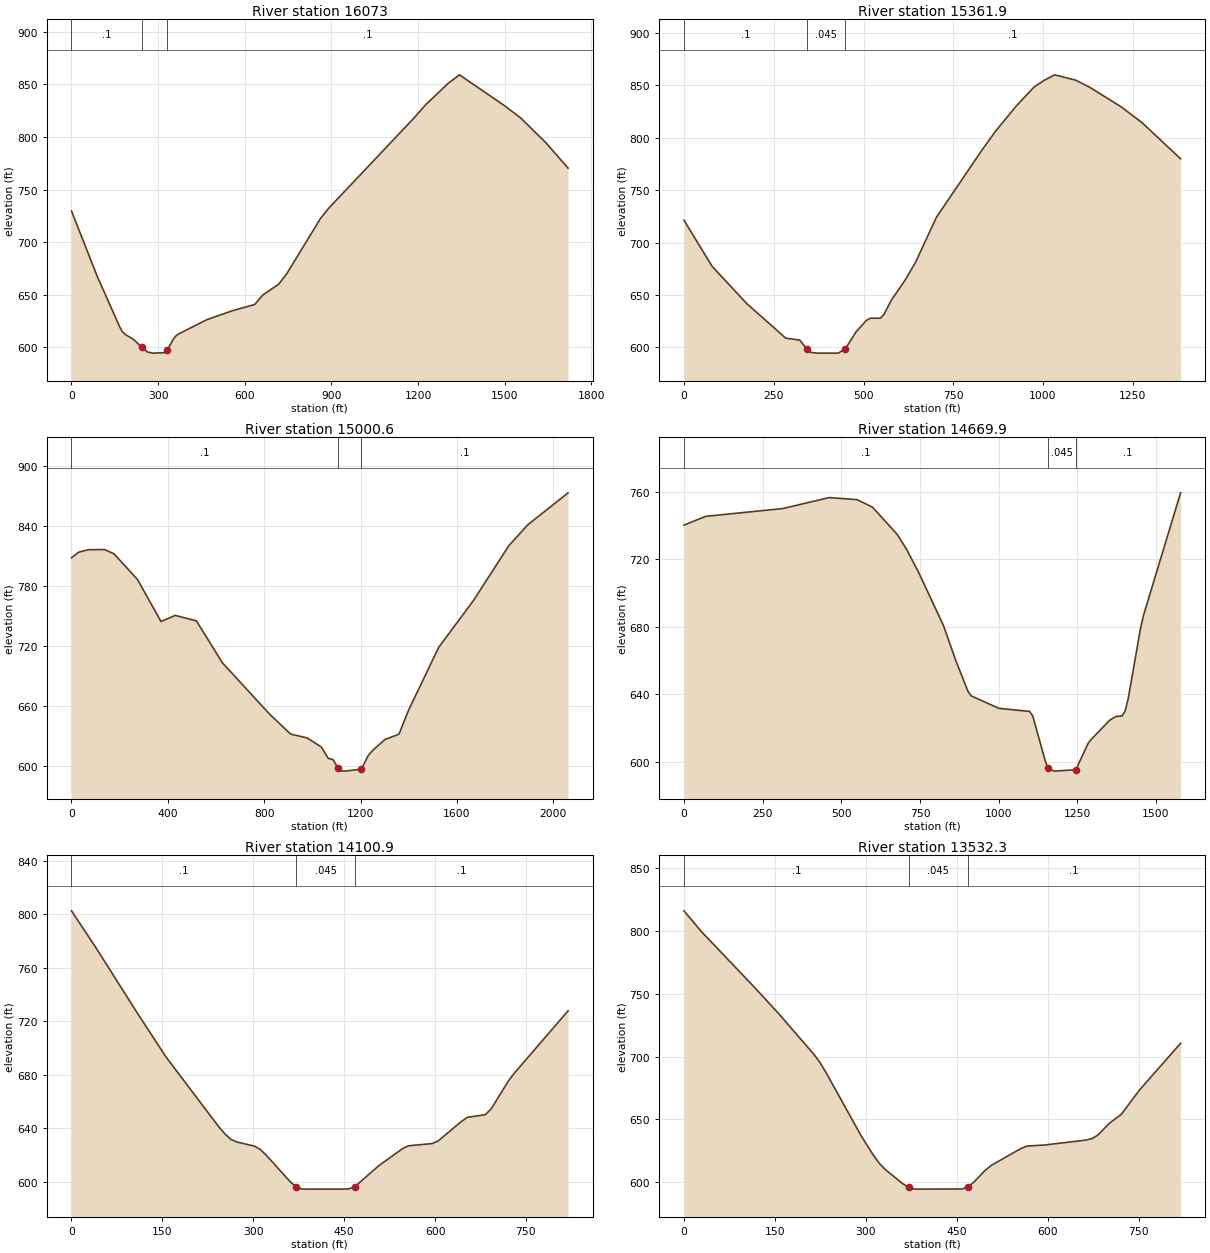
Type RM Length L Ch R = 1 ,16073   ,681,711.1,741.2
XS GIS Cut Line= 5
     1740815.386      452603.725     1741375.803      452880.808
     1741354.969      453018.308     1741138.303      453555.808
     1741323.719      453882.891
#Sta/Elev= 30
       0  729.69    87.9  668.29   166.1  619.89   175.8   614.9   185.6  612.26
   214.9  607.46   244.2  599.79   263.8  595.33   283.3   594.4   322.4  594.85
   332.1  597.47   351.7  607.22   361.4  610.81   371.2  612.69   468.9  626.24
   556.8  634.69   634.4  640.66   662.3  649.62   717.9  660.04   745.7  670.02
   862.5  722.59   891.9  732.59  1186.6  818.23  1225.9  830.53  1304.5  851.08
  1343.8  859.18    1498  830.13  1555.9  818.09  1642.6  794.68  1719.8  770.41
#Mann= 3 , 0 , 0
       0      .1       0   244.2    .045       0   332.1      .1       0
Bank Sta=244.2,332.1
XS Rating Curve= 0 ,0
Exp/Cntr=0.3,0.1

Type RM Length L Ch R = 1 ,15361.9 ,360,361.3,362.6
XS GIS Cut Line= 4
     1740377.886      452945.391     1740779.969      453474.558
     1741120.733      453613.702     1741292.608      453919.257
#Sta/Elev= 30
       0   721.3    78.2  677.34   175.9  641.33   283.4  608.73   322.5  606.84
   342.1  598.34   351.8  595.19   371.4   594.4     430  594.42   449.6   598.6
   478.9  614.57   508.2   625.7     518   627.7   547.3  627.78   557.1  631.39
   576.6  644.44   615.7  664.02     645  681.19   703.3  724.25   829.3     788
     868  806.44   926.1  830.64   974.6  848.35  1003.6  855.02  1032.7  860.18
  1091.1  855.06  1130.1  848.31  1217.7  829.62  1276.1  814.43  1383.2  780.02
#Mann= 3 , 0 , 0
       0      .1       0   342.1    .045       0   449.6      .1       0
Bank Sta=342.1,449.6
XS Rating Curve= 0 ,0
Exp/Cntr=0.3,0.1

Type RM Length L Ch R = 1 ,15000.6 ,342.1,330.7,319.4
XS GIS Cut Line= 5
     1739444.553      452859.975     1739952.886      452962.058
     1740471.023      453673.599     1740406.358      453985.669
     1740431.358      454328.725
#Sta/Elev= 30
       0  808.29    29.4   813.8    68.5  816.35     137  816.51   176.1   812.3
   273.9  786.54   371.7  744.35   430.4  750.52   518.5  745.03   626.1  703.11
   821.7  651.71   909.7   631.5   978.1  627.71  1036.8  618.64  1066.2  607.15
  1085.7  605.99  1105.3  597.91  1115.1  594.76  1134.6   594.4  1203.1  596.35
  1232.4  610.28    1252  615.62  1300.9  626.04  1359.6  631.48  1398.7  655.16
  1524.2  718.45  1669.1  765.59  1815.7   820.5  1894.3  841.36  2061.4  873.39
#Mann= 3 , 0 , 0
       0      .1       0  1105.3    .045       0  1203.1      .1       0
Bank Sta=1105.3,1203.1
XS Rating Curve= 0 ,0
Exp/Cntr=0.3,0.1

Type RM Length L Ch R = 1 ,14669.9 ,573.5,569,563.3
XS GIS Cut Line= 3
     1738997.469      453665.785     1739835.379      453456.401
       1740349.9      453952.243
#Sta/Elev= 30
       0  740.24    68.7  745.44   314.1  750.07   461.3  756.56   549.6  755.37
   598.7  750.97   677.2  734.81   706.6  726.17   745.9  712.14   824.4  680.83
   863.7     660   902.8  641.61   912.6  639.03  1000.7  631.64  1098.6  629.78
  1108.4  627.09  1147.5  600.86  1157.3  595.98  1176.9   594.4  1245.4  595.24
  1284.6  610.96  1294.4  613.25  1353.1  624.61  1372.7  626.81  1392.2  627.07
    1402  630.06  1411.8  637.42    1451  679.19  1460.8  687.03  1578.2  759.39
#Mann= 3 , 0 , 0
       0      .1       0  1157.3    .045       0  1245.4      .1       0
Bank Sta=1157.3,1245.4
XS Rating Curve= 0 ,0
Exp/Cntr=0.3,0.1

Type RM Length L Ch R = 1 ,14100.9 ,576.1,568.6,561
XS GIS Cut Line= 3
     1739375.075      453841.234     1739688.414      454104.598
     1740007.544       454362.23
#Sta/Elev= 30
       0  802.67      39  776.03   107.2  727.19   155.9  693.35   243.6  640.76
   253.4  635.66   263.1   631.6   272.9  629.66   302.1  626.58   311.9  623.96
   321.6  619.71   360.6   600.1   370.3  596.24   380.1  594.48   389.8   594.4
   448.4   594.4   458.2  594.65   467.9  596.34     507  611.89     546  624.62
   555.8  626.81   594.9   628.5   604.6  630.31   643.7  645.11   653.4  648.16
   682.8  650.09   692.5  654.42   721.8  675.87   731.6   681.6   819.5  727.84
#Mann= 3 , 0 , 0
       0      .1       0   370.3    .045       0   467.9      .1       0
Bank Sta=370.3,467.9
XS Rating Curve= 0 ,0
Exp/Cntr=0.3,0.1

Type RM Length L Ch R = 1 ,13532.3 ,547.4,524.1,502
XS GIS Cut Line= 3
     1739025.887      454349.314     1739368.097      454574.194
     1739714.274      454793.088
#Sta/Elev= 30
       0     816    29.2  799.25     117  754.71     156  734.25   214.5   701.6
   224.2  695.27     234  687.44   292.5  636.63     312   621.7   321.7  615.16
   331.5  610.23   360.7  598.74   370.5  595.73   380.2  594.46     390   594.4
   458.2  594.54     468  595.99   477.8  599.87   497.2  609.56     507  613.34
   555.8  626.77   565.5  628.68   594.8  629.53     663  633.47   672.8  634.61
   682.5   637.4     702  646.97   721.5  654.02   750.8  673.02   819.1  710.51
#Mann= 3 , 0 , 0
       0      .1       0   370.5    .045       0     468      .1       0
Bank Sta=370.5,468
XS Rating Curve= 0 ,0
Exp/Cntr=0.3,0.1

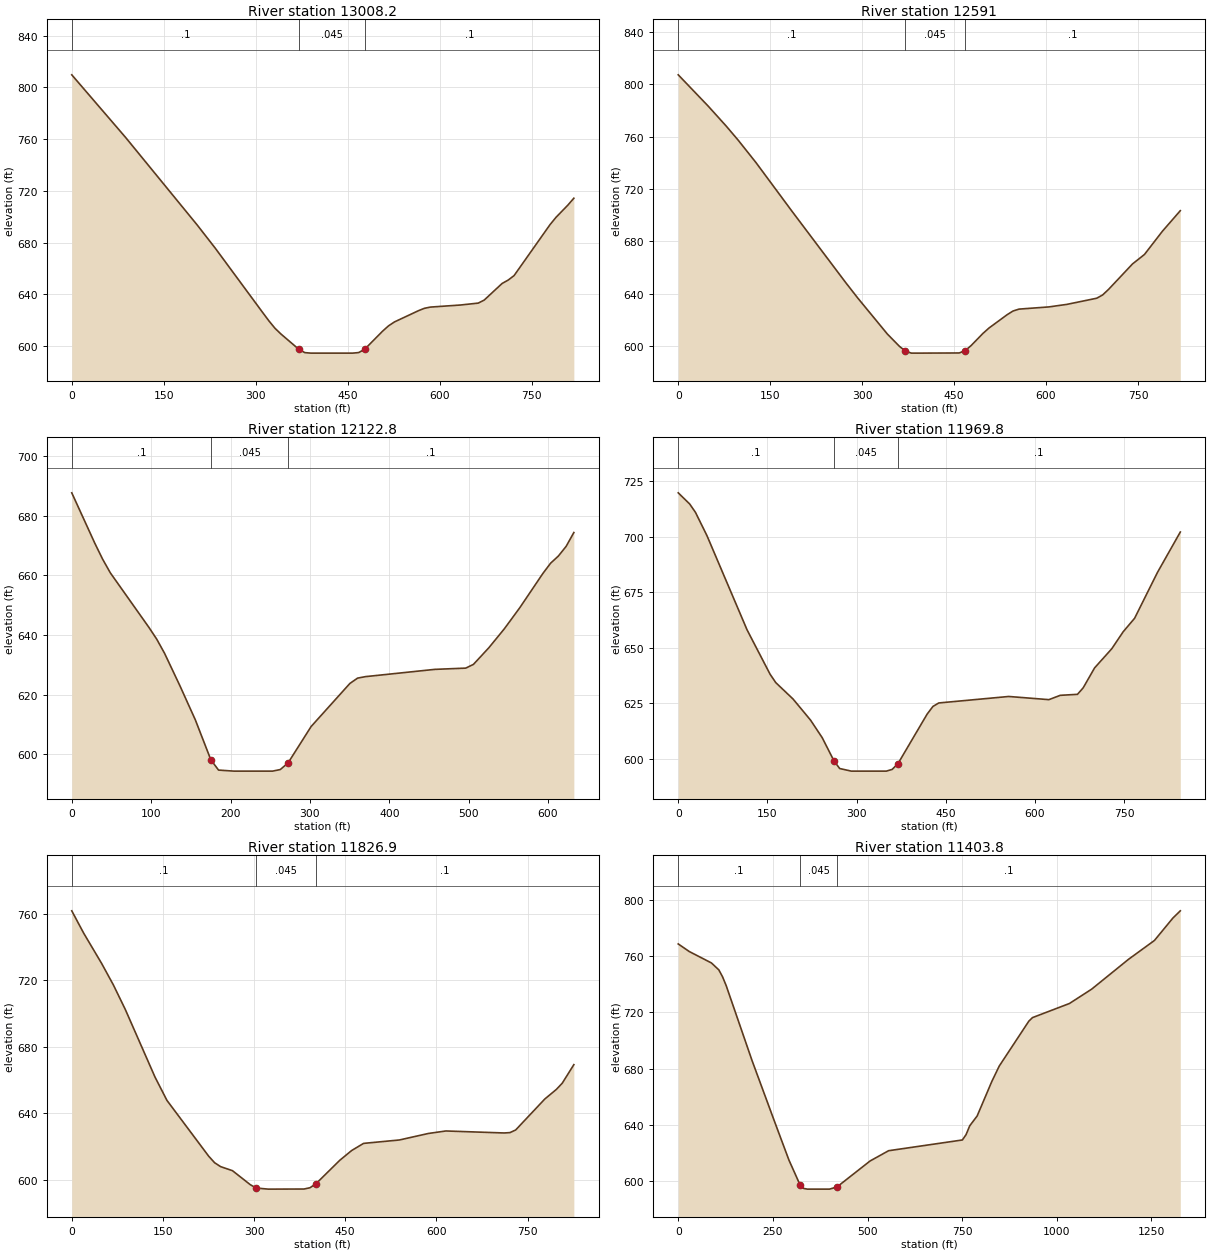
Type RM Length L Ch R = 1 ,13008.2 ,423.5,417.2,410.9
XS GIS Cut Line= 3
      1738782.79      454970.968     1739182.067      455061.899
     1739581.344      455152.829
#Sta/Elev= 30
       0  809.75    87.8  761.31   204.8  693.44     234  675.65     312  625.45
   321.8  619.22   331.5  613.63   341.2   609.2   370.5  597.32   380.2  594.79
     390   594.4   458.2   594.4     468  594.82   477.8  597.38     507  611.38
   516.8  615.53   526.5  618.57   565.5  627.23   575.2  629.07     585  630.02
   633.8  631.62     663   633.1   672.8  635.45     702  648.32   711.8  650.89
   721.5  654.39     780  693.72   789.8  699.43   809.2   708.9     819  714.26
#Mann= 3 , 0 , 0
       0      .1       0   370.5    .045       0   477.8      .1       0
Bank Sta=370.5,477.8
XS Rating Curve= 0 ,0
Exp/Cntr=0.3,0.1

Type RM Length L Ch R = 1 ,12591   ,504.1,468.2,432.2
XS GIS Cut Line= 3
     1738719.161      455422.991     1739125.368      455474.815
     1739531.576      455526.639
#Sta/Elev= 30
       0  807.31    48.8  783.41      78  768.24    97.5  757.48   126.8  740.19
   185.2  703.17     273  648.48   292.5  636.75   341.2  608.98   360.8  599.62
   370.5  595.95   380.2  594.41     390   594.4   458.2  594.52     468  596.25
   477.8   600.2   497.2  609.54     507  613.63   536.2  623.69     546  626.58
   555.8  628.07   604.5  629.75   633.8  631.68   682.5  636.38   692.2  638.87
     702  643.18     741  662.62   760.5  669.87   789.8  687.65     819  703.38
#Mann= 3 , 0 , 0
       0      .1       0   370.5    .045       0     468      .1       0
Bank Sta=370.5,468
XS Rating Curve= 0 ,0
Exp/Cntr=0.3,0.1

Type RM Length L Ch R = 1 ,12122.8 ,117.9,153.1,188.4
XS GIS Cut Line= 2
     1738985.317      456019.952     1739561.705      455759.535
#Sta/Elev= 30
       0  687.72    29.2  670.72    38.9  665.46    48.6  660.88    97.3  642.56
     107  638.66   116.8  633.96   136.2  623.05   155.7  611.57   175.2   598.2
   184.9  594.75   204.3   594.4     253   594.4   262.7  594.93   272.5  597.16
   301.6  609.38   350.3  623.78     360  625.58   369.8  626.08   457.3  628.52
   496.3  628.94     506  630.19   525.4  635.76   544.9  642.11   564.4  649.19
   593.6  660.72   603.3  664.14     613  666.52   622.8  669.77   632.5   674.4
#Mann= 3 , 0 , 0
       0      .1       0   175.2    .045       0   272.5      .1       0
Bank Sta=175.2,272.5
XS Rating Curve= 0 ,0
Exp/Cntr=0.3,0.1

Type RM Length L Ch R = 1 ,11969.8 ,141.8,142.8,143.8
XS GIS Cut Line= 4
     1738938.135      456067.701     1739121.468      456063.534
     1739502.718      456093.743      1739735.01      455939.576
#Sta/Elev= 30
       0  719.66    19.3  714.62      29  710.86    48.3   700.4   115.8  657.98
   154.4  638.07   164.1  634.23   193.2  626.84   222.6  617.35   242.2  609.45
   261.8  599.12   271.6  595.57   291.2   594.4   350.1   594.4   359.9  595.18
   369.7  597.79   418.7  620.06   428.5  623.52   438.3  625.08     556     628
   623.5  626.57   642.7  628.52   671.6  628.96   681.2  631.89   700.4  640.86
   729.3  649.48   748.5  657.13   767.7  663.19   806.2  683.85   844.6  702.02
#Mann= 3 , 0 , 0
       0      .1       0   261.8    .045       0   369.7      .1       0
Bank Sta=261.8,369.7
XS Rating Curve= 0 ,0
Exp/Cntr=0.3,0.1

Type RM Length L Ch R = 1 ,11826.9 ,483.6,423.1,362.5
XS GIS Cut Line= 4
     1738981.885      456264.576     1739119.385      456189.576
     1739500.635      456219.784     1739740.218      456061.451
#Sta/Elev= 30
       0   761.9    19.6  748.46      49  730.33    68.5  717.28    88.1  702.53
     137  661.83   156.6  647.82   225.3  614.23   235.1  610.28   244.9  607.95
   264.5  605.49   293.9  597.04   303.7  595.05   323.3   594.4   382.2  594.46
     392  595.24   401.8  597.63     441  611.74   460.6  617.64   480.2  621.93
   539.1  623.98   586.9   627.9   615.6   629.4   711.4   628.2     721  628.41
   730.5  630.01   778.4  648.63   797.5  654.43   807.1  658.15   826.2  669.31
#Mann= 3 , 0 , 0
       0      .1       0   303.7    .045       0   401.8      .1       0
Bank Sta=303.7,401.8
XS Rating Curve= 0 ,0
Exp/Cntr=0.3,0.1

Type RM Length L Ch R = 1 ,11403.8 ,569.9,569,568.2
XS GIS Cut Line= 3
     1739273.711      456819.297     1739926.896      456149.292
     1740014.396      455768.736
#Sta/Elev= 30
       0  768.46    29.2  763.06    87.7  754.96   107.2  750.06     117  745.16
   126.7  738.84   194.9  685.73   253.4   643.1   292.4  615.05   321.6  597.52
   331.4  594.89   341.2   594.4   399.6   594.4   419.1   595.9   506.8  614.38
   555.6  621.66   750.5  629.29   760.3  633.08     770  639.37   789.5  646.29
   828.5  670.93     848  681.79     926   713.6   935.7  716.15  1033.3  726.17
  1091.9  736.33  1189.5  757.56  1257.9  770.93  1306.7  786.85  1326.2  791.96
#Mann= 3 , 0 , 0
       0      .1       0   321.6    .045       0   419.1      .1       0
Bank Sta=321.6,419.1
XS Rating Curve= 0 ,0
Exp/Cntr=0.3,0.1

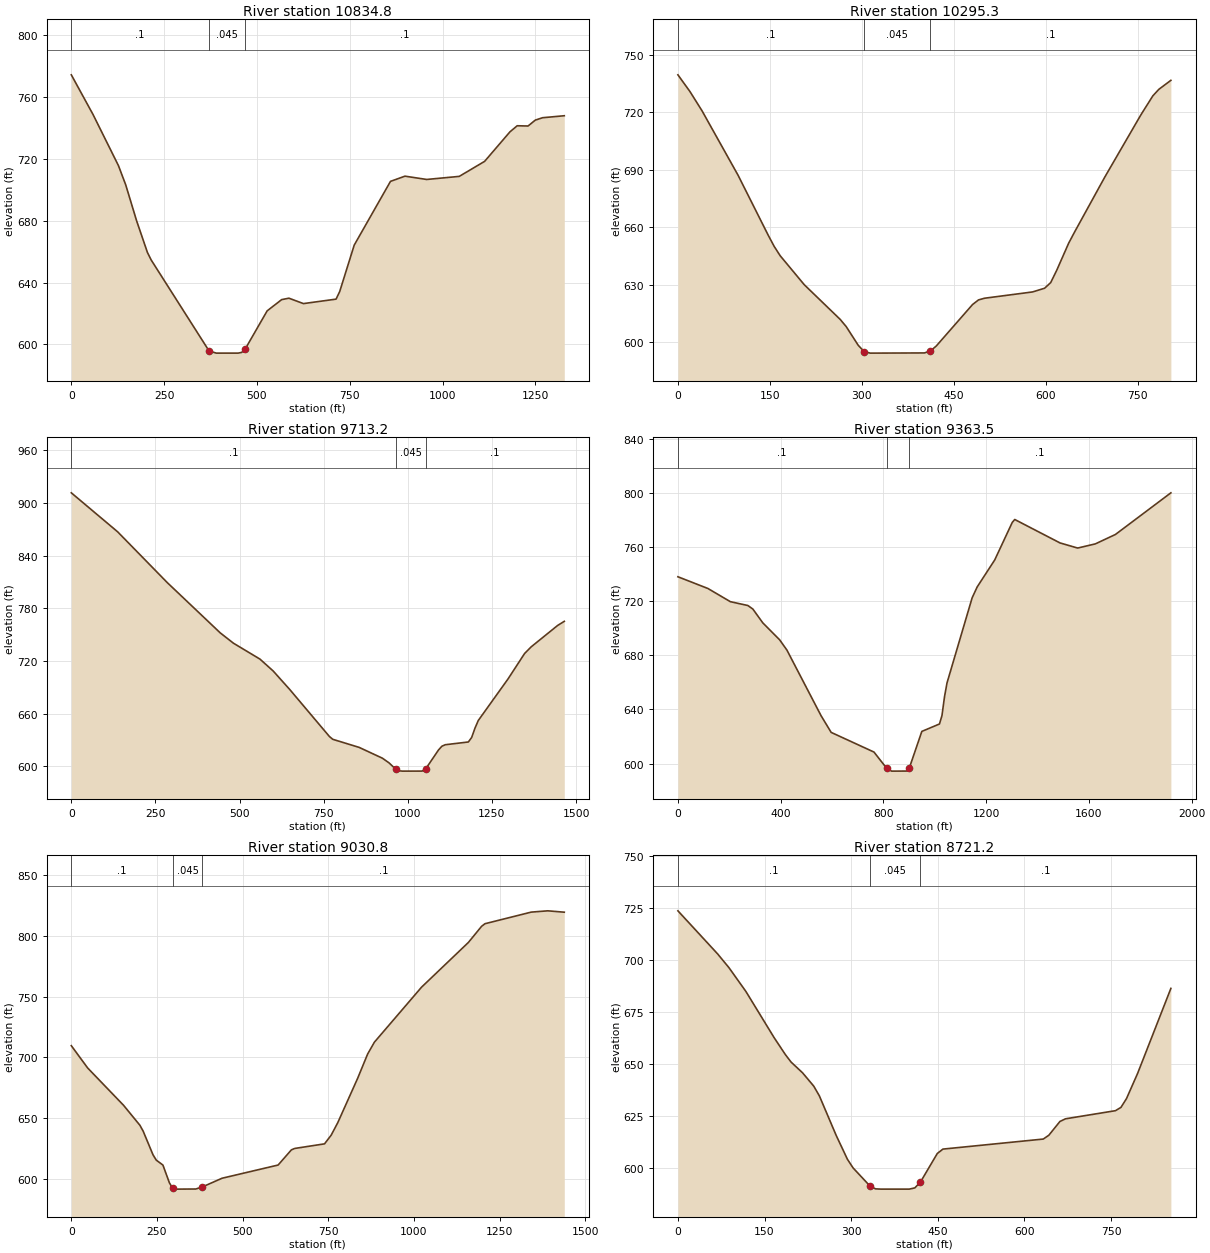
Type RM Length L Ch R = 1 ,10834.8 ,547.8,539.4,531.1
XS GIS Cut Line= 3
     1739690.785      457211.792     1740303.285      456567.347
      1740722.73      456438.181
#Sta/Elev= 30
       0  774.25    58.6  748.57     127  715.56   146.6  703.13   175.9  679.92
   205.2  659.36   214.9   654.7   371.3  595.74   390.8   594.4   449.4  594.41
   459.1  594.88     469  597.29   527.6  621.72   566.7  628.99   586.2   629.9
   625.3  626.41   713.2  629.29     723  634.18   762.1   664.2   859.8  705.39
   898.8  708.76   957.4  706.63  1045.1  708.62  1113.4  718.33  1181.7  737.42
  1201.2  741.34  1230.4  741.17  1249.9  744.98  1269.4  746.52    1328  747.81
#Mann= 3 , 0 , 0
       0      .1       0   371.3    .045       0     469      .1       0
Bank Sta=371.3,469
XS Rating Curve= 0 ,0
Exp/Cntr=0.3,0.1

Type RM Length L Ch R = 1 ,10295.3 ,577.6,582.1,586.7
XS GIS Cut Line= 2
     1740193.563      457525.681     1740668.563       456877.07
#Sta/Elev= 30
       0  739.54    19.6  730.83    39.2  720.85      98  687.23   147.1     656
   156.9  650.11   166.7  645.22   205.9  630.13   264.7  611.97   274.5   608.2
   294.1  598.47   303.9  595.14   313.7   594.4     402   594.5   411.8   595.5
   421.6  598.21   480.4  619.72   490.2  622.15     500  623.03   578.4  626.31
     598  628.25   607.9  631.18   617.7  637.58   637.3   651.8   647.1   657.7
   696.1   686.2   754.9  718.63   774.5  728.58   784.3  731.98   803.9  736.67
#Mann= 3 , 0 , 0
       0      .1       0   303.9    .045       0   411.8      .1       0
Bank Sta=303.9,411.8
XS Rating Curve= 0 ,0
Exp/Cntr=0.3,0.1

Type RM Length L Ch R = 1 ,9713.2  ,348.4,349.7,351.2
XS GIS Cut Line= 3
     1740065.785      458079.847     1740697.622      457782.451
     1741192.174      457196.514
#Sta/Elev= 30
       0  911.71   137.7  867.26   285.2  809.35   442.6  752.04   481.9  740.25
   560.6  722.14     600  708.55   649.2  687.47   767.1  633.87     777  630.69
   855.6  621.44   924.4  609.17   944.1  603.87   963.7  596.82   973.6  594.83
   983.4   594.4  1042.4  594.44  1053.2  596.96  1091.5  618.63  1101.4   622.8
  1111.2  624.48    1180  627.64  1189.8  632.76  1199.7  643.38  1209.5  652.13
    1298  699.56  1347.1   728.5  1366.8  736.12  1445.4  760.51  1465.1  765.19
#Mann= 3 , 0 , 0
       0      .1       0   963.7    .045       0  1053.2      .1       0
Bank Sta=963.7,1053.2
XS Rating Curve= 0 ,0
Exp/Cntr=0.3,0.1

Type RM Length L Ch R = 1 ,9363.5  ,288.1,332.7,377.1
XS GIS Cut Line= 6
     1740739.396      458486.792      1740897.73      458207.625
     1740943.563      458015.959     1741340.785      457568.736
     1741400.508      457372.903     1741369.952      456775.681
#Sta/Elev= 30
       0  738.08   116.7  729.42   204.2  719.66   272.3  716.82   291.8   714.2
   330.3  704.03     396  691.46   424.2  683.92   557.2  635.38   596.5  623.04
   763.2  608.49   812.2  596.61   831.8   594.4   890.6  594.44   900.4  596.51
   949.5  623.77  1018.1  629.25  1027.9  635.54  1037.7  649.38  1047.5  659.63
  1145.4  722.57  1164.9  730.56  1233.2  750.51  1301.4  778.24  1311.2  780.41
  1487.6  763.07  1556.2  759.31  1624.8  762.38  1703.2  769.36  1918.9  800.13
#Mann= 3 , 0 , 0
       0      .1       0   812.2    .045       0   900.4      .1       0
Bank Sta=812.2,900.4
XS Rating Curve= 0 ,0
Exp/Cntr=0.3,0.1

Type RM Length L Ch R = 1 ,9030.8  ,324.6,309.7,294.7
XS GIS Cut Line= 6
     1740903.285      458247.903     1741061.619      458110.403
     1741411.619      458050.681     1741696.341      457956.236
     1741942.174      457954.847     1742267.174      457999.292
#Sta/Elev= 30
       0  709.49    47.7  691.13   152.5  660.36   200.2   643.9   209.7  639.05
   238.5  619.53   248.1  615.15   267.3  611.15   286.5  596.33   296.1     592
   305.7   591.3   363.2   591.4   382.4  593.11     440  600.28   603.5  611.15
   642.2  623.64   651.8  624.81   738.9   628.6   758.3  635.74   777.6  646.08
   835.7  682.67   864.7   702.6   884.4  712.36  1022.1  757.71  1158.8  794.56
  1197.4  807.88  1207.1  809.98  1342.1  819.55  1390.4  820.61  1438.6  819.48
#Mann= 3 , 0 , 0
       0      .1       0   296.1    .045       0   382.4      .1       0
Bank Sta=296.1,382.4
XS Rating Curve= 0 ,0
Exp/Cntr=0.3,0.1

Type RM Length L Ch R = 1 ,8721.2  ,539.6,536.5,533.3
XS GIS Cut Line= 4
     1741038.008      458581.236     1741183.971      458422.345
     1741479.674      458297.903     1741767.174       458164.57
#Sta/Elev= 30
       0   723.7    68.6  703.02    88.3  696.38   117.7  684.91   166.7  662.63
   186.3  654.43   196.1  650.88   215.8  645.77   235.2  639.35   244.9  634.68
   274.1   615.6   293.5  604.16   303.3     600   332.4  591.33   342.1  589.93
   351.9   589.8   400.5   589.8   410.2   590.4   419.9   593.2   449.1  606.95
   458.8  609.06   632.6  613.89   642.2  615.73   661.4  622.35     671  623.63
   757.5  627.54   767.1  629.14   776.7  633.39   795.9  645.48   853.5  686.38
#Mann= 3 , 0 , 0
       0      .1       0   332.4    .045       0   419.9      .1       0
Bank Sta=332.4,419.9
XS Rating Curve= 0 ,0
Exp/Cntr=0.3,0.1

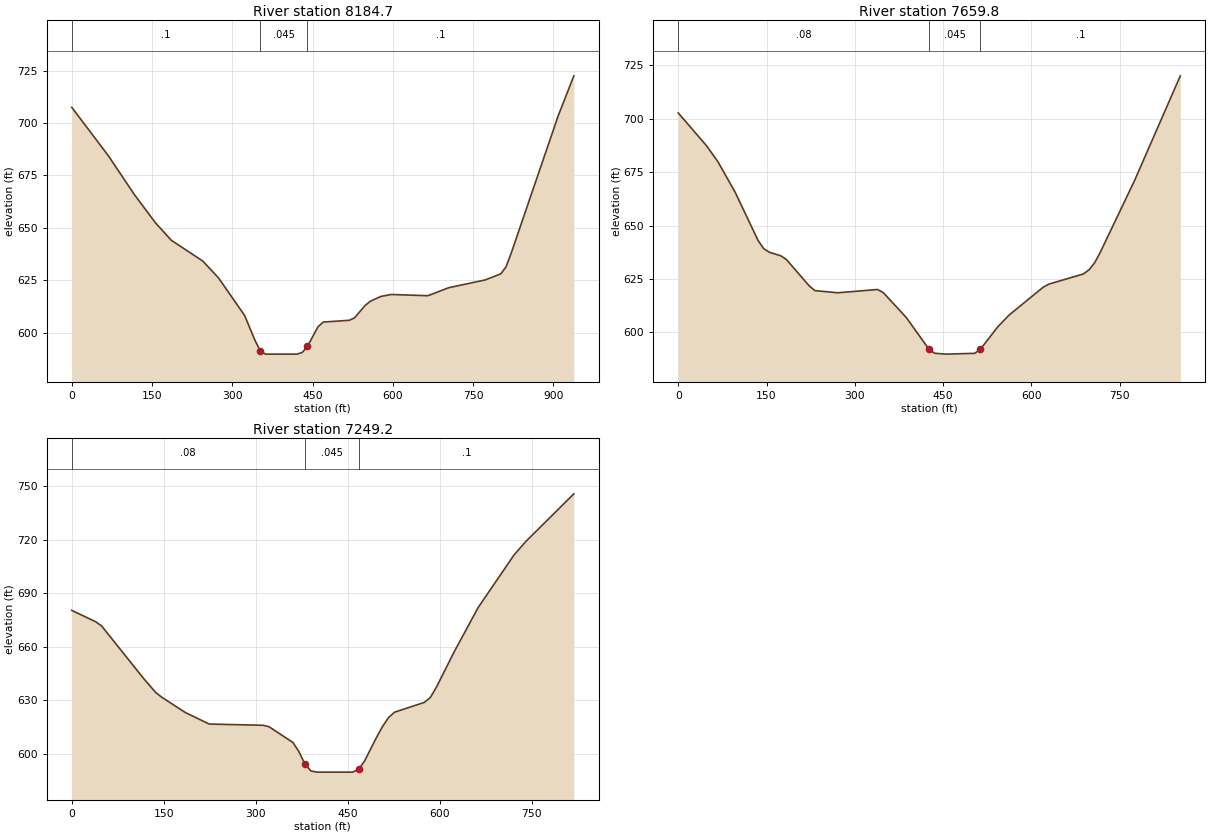
Type RM Length L Ch R = 1 ,8184.7  ,521.5,524.9,528.3
XS GIS Cut Line= 3
     1741171.341      459029.847     1741744.952      458754.847
     1742026.896      458646.514
#Sta/Elev= 30
       0   707.5    68.5  684.36   117.4  665.74   156.6  652.37   185.9  644.12
   244.7  634.21     274  626.22     323  608.24   342.5   596.3   352.3  591.36
   362.1   589.8   420.8   589.8   430.6  590.58   440.4  593.46     460  602.81
   469.8  605.08   518.7  605.94   528.5  607.13     548  612.98   557.8     615
   577.4   617.3     597  618.24   665.4  617.65   704.3  621.47   772.5  625.18
   801.8  628.09   811.5  631.46   821.2  637.99   908.9  703.42   938.2  722.52
#Mann= 3 , 0 , 0
       0      .1       0   352.3    .045       0   440.4      .1       0
Bank Sta=352.3,440.4
XS Rating Curve= 0 ,0
Exp/Cntr=0.3,0.1

Type RM Length L Ch R = 1 ,7659.8  ,384.9,410.7,436.4
XS GIS Cut Line= 3
     1741294.952      459431.236     1741621.112       459388.59
     1742104.674      459186.792
#Sta/Elev= 30
       0  702.75    48.4  687.27    67.7  679.77    96.8  665.55   135.4  643.14
   145.1   639.2   154.8   637.5   174.1  635.86   183.8   634.1   222.5  621.76
   232.2  619.54   270.9  618.53   338.6  620.06   348.3  618.61   387.2  607.02
     426  592.09   435.7   590.2   455.1   589.8   503.6  590.17   513.3   592.1
   542.4  602.43   561.8  608.04     620  621.14   629.7  622.59     688  627.32
   697.7  629.24   707.4  632.57   717.1  637.56   775.3  671.14   852.9  720.11
#Mann= 3 , 0 , 0
       0     .08       0     426    .045       0   513.3      .1       0
Bank Sta=426,513.3
XS Rating Curve= 0 ,0
Exp/Cntr=0.3,0.1

Type RM Length L Ch R = 1 ,7249.2  ,475.5,471.2,466.8
XS GIS Cut Line= 3
     1741389.032      459739.557     1741798.532      459739.557
     1742208.032      459739.557
#Sta/Elev= 30
       0  680.46      39  674.12    48.8  671.69     117  642.38   136.5  634.61
   146.2  631.92   185.2  623.22   224.2  616.75     312  616.06   321.8  615.25
   360.8  606.41   370.5  601.28   380.2  594.44     390  590.49   399.8   589.8
   458.2   589.8     468  591.35   477.8  596.14   497.2  609.33     507   615.4
   516.8  620.42   526.5   623.4   575.2   628.9     585  631.68   594.8  637.39
     624  657.36     663   682.1   721.5  711.57     741   719.2     819   745.8
#Mann= 3 , 0 , 0
       0     .08       0   380.2    .045       0     468      .1       0
Bank Sta=380.2,468
XS Rating Curve= 0 ,0
Exp/Cntr=0.3,0.1