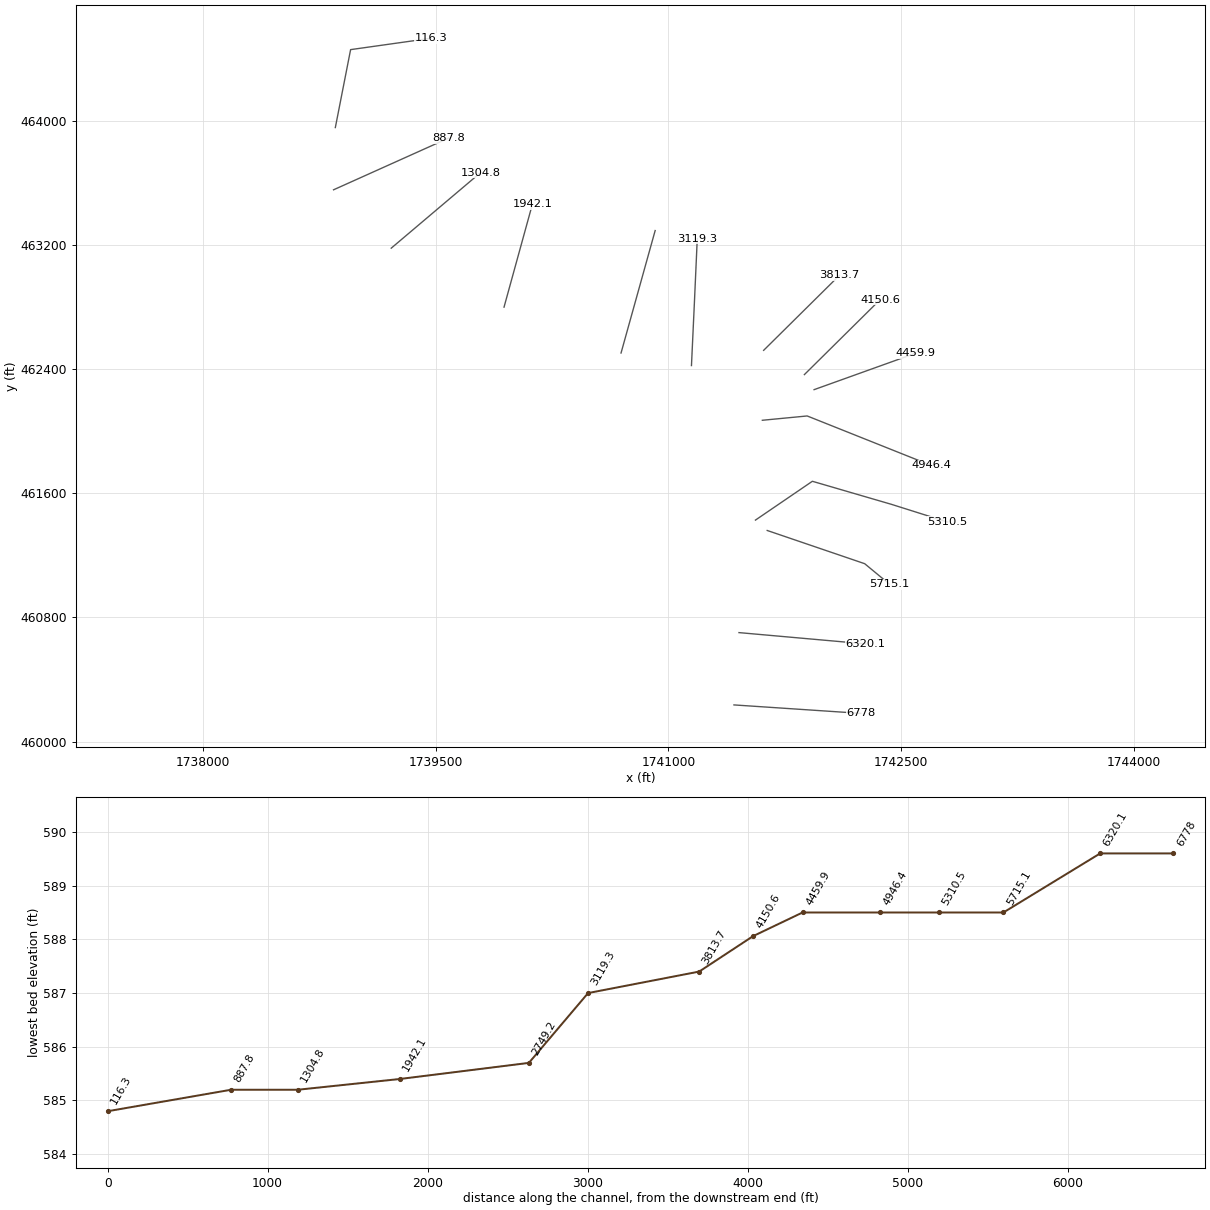
HEC-RAS study BIGCOALRIV.prj: BIGCOALRIV

--- BIGCOALRIV.g01 (geometry) --- (continued)

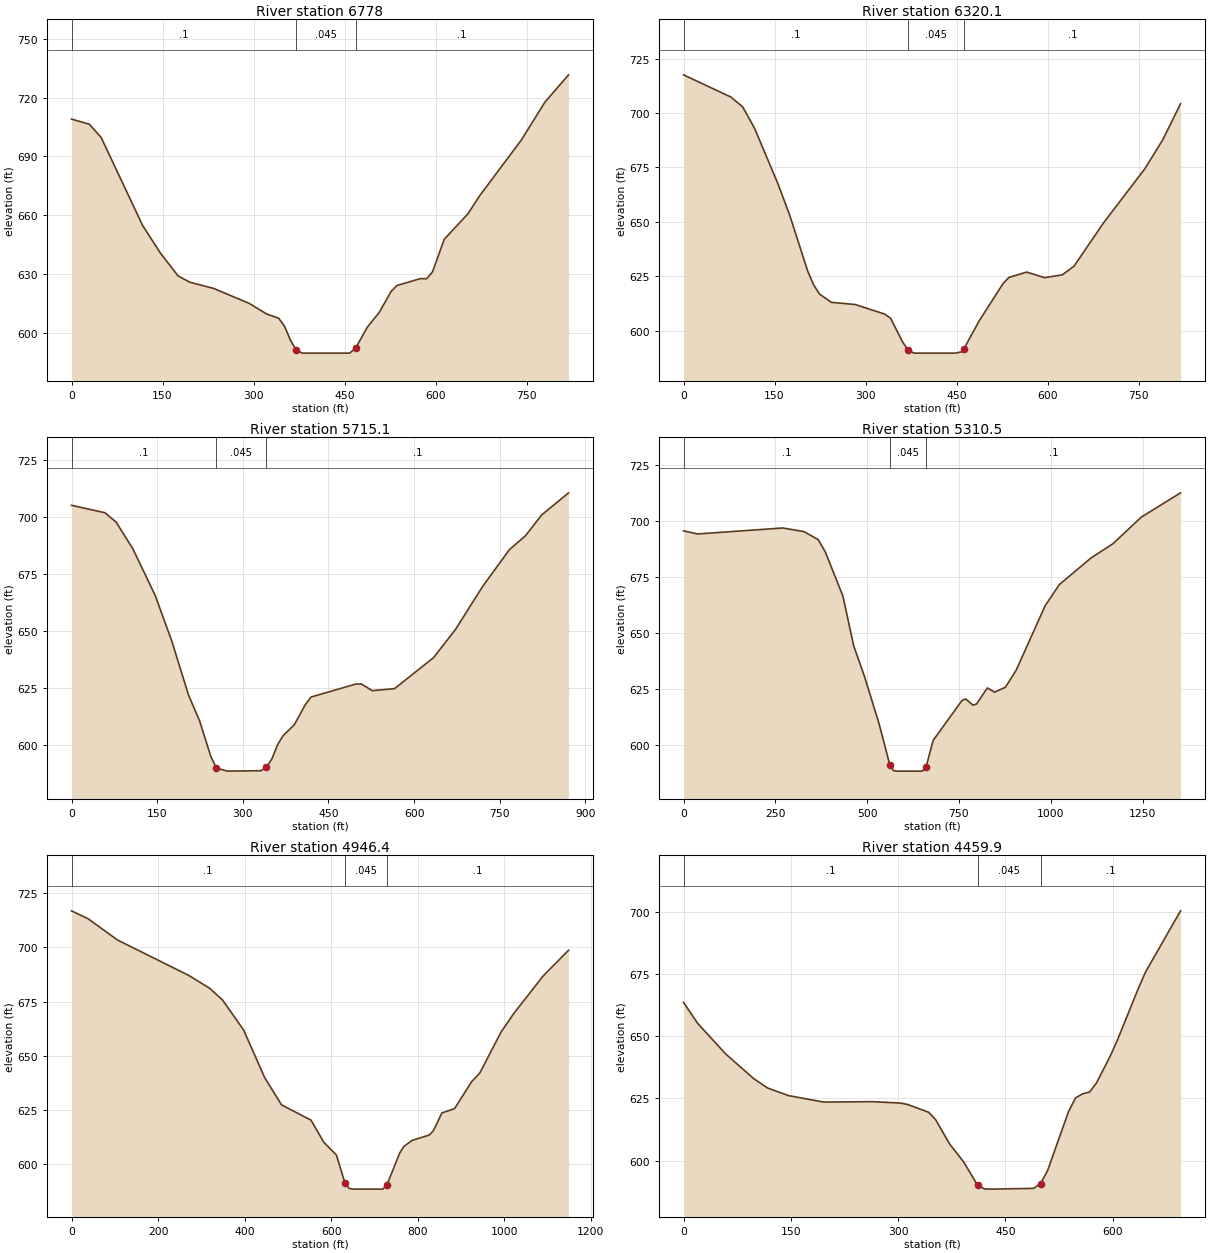
Type RM Length L Ch R = 1 ,6778    ,459.3,457.9,456.5
XS GIS Cut Line= 3
      1741422.28      460236.663     1741830.873      460209.423
     1742239.466      460182.183
#Sta/Elev= 30
       0  709.01    29.2  706.42    48.8  699.66     117  654.84   146.2  640.76
   175.5  629.04     195  625.76     234  622.63   292.5  615.03   321.8  609.52
   341.2  607.44     351  603.36   360.8  596.21   370.5  591.05   380.2   589.6
   458.2   589.6     468  592.07   487.5  602.89     507  610.35   526.5  621.02
   536.2   624.1   575.2  627.65     585  627.55   594.8  631.04   614.2  647.72
   653.2  660.67   672.8  670.02     741  698.25     780  717.61     819  731.59
#Mann= 3 , 0 , 0
       0      .1       0   370.5    .045       0     468      .1       0
Bank Sta=370.5,468
XS Rating Curve= 0 ,0
Exp/Cntr=0.3,0.1

Type RM Length L Ch R = 1 ,6320.1  ,620.6,605,589.4
XS GIS Cut Line= 3
     1741454.676      460702.486     1741862.564       460666.19
     1742270.453      460629.895
#Sta/Elev= 30
       0  717.61      78   707.4    97.5  702.86     117  693.06     156  667.21
   175.5   652.6   204.8  627.19   214.5  620.95   224.2  616.74   243.8  612.95
   282.8  611.97   331.5  607.56   341.2  605.65   360.8  594.84   370.5  590.83
   380.2   589.6   448.5   589.6   458.2  590.22   462.1  591.67   487.5  604.57
   526.5   621.6   536.2  624.42   565.5  626.88   594.8  624.31     624   625.6
   643.5  629.62   692.2  649.55   760.5  674.54   789.8   687.8     819  704.34
#Mann= 3 , 0 , 0
       0      .1       0   370.5    .045       0   462.1      .1       0
Bank Sta=370.5,462.1
XS Rating Curve= 0 ,0
Exp/Cntr=0.3,0.1

Type RM Length L Ch R = 1 ,5715.1  ,401.3,404.6,407.4
XS GIS Cut Line= 3
     1741636.619      461360.403     1742264.396      461146.514
     1742424.119       461014.57
#Sta/Elev= 30
       0  705.18    58.5  701.92      78  697.83   107.3  686.13   146.3  665.76
   175.6   645.6   204.8  621.98   224.3  610.54   243.8  595.05   253.6  589.84
   273.1   588.5   331.6  588.69   341.4  590.14   351.1  593.99   360.9   600.1
   370.6  604.08   390.1  608.86   409.6  617.72   419.4  621.01   497.4  626.69
   507.2  626.79   526.7  623.83   565.7   624.7     634  638.33   672.6  650.74
   719.7  669.48   766.8   685.7     795  691.82   823.3  700.94   870.4  710.65
#Mann= 3 , 0 , 0
       0      .1       0   253.6    .045       0   341.4      .1       0
Bank Sta=253.6,341.4
XS Rating Curve= 0 ,0
Exp/Cntr=0.3,0.1

Type RM Length L Ch R = 1 ,5310.5  ,370.7,364.1,357.9
XS GIS Cut Line= 4
     1741560.739      461427.347     1741927.406      461677.347
     1742437.128      461528.736     1742798.239      461414.847
#Sta/Elev= 30
       0  695.48    38.6   694.1   270.1  696.77     328  695.16   366.6   691.6
   385.9  686.18   434.1   666.4   463.4  644.28     493  630.54   532.3   609.7
   561.8  591.27   571.6  588.72   581.4   588.5   650.3   588.5   660.1  590.18
   679.8  602.19   758.4     620   768.2  620.64   787.9   617.9   797.8  618.39
   827.2  625.53   846.9  623.67   876.4  625.83   905.9  633.48   984.4  662.06
  1023.3  671.58  1110.6  683.54  1168.9   689.7  1246.6  701.61  1353.4  712.42
#Mann= 3 , 0 , 0
       0      .1       0   561.8    .045       0   660.1      .1       0
Bank Sta=561.8,660.1
XS Rating Curve= 0 ,0
Exp/Cntr=0.3,0.1

Type RM Length L Ch R = 1 ,4946.4  ,439.3,486.5,533.7
XS GIS Cut Line= 3
     1741605.183      462070.403     1741894.072      462098.181
     1742691.295      461780.125
#Sta/Elev= 30
       0  716.88    38.7  713.18   106.4  703.41   270.9  687.09   319.5  681.12
   348.7  675.82   397.5  661.98   446.3  639.98   485.3  627.37   553.6   620.3
   582.8  610.17   612.1  604.24   631.6  591.54   641.4  588.85   651.1   588.5
   719.4   588.5   729.1  590.57   758.4  605.14   768.2  608.25   787.7  611.03
   826.7  613.45   836.4  615.48   855.9  623.65   885.2  625.64   924.2  637.96
   943.7  642.12   992.5  660.92  1021.8  669.47    1090  686.87  1148.6  698.69
#Mann= 3 , 0 , 0
       0      .1       0   631.6    .045       0   729.1      .1       0
Bank Sta=631.6,729.1
XS Rating Curve= 0 ,0
Exp/Cntr=0.3,0.1

Type RM Length L Ch R = 1 ,4459.9  ,281.1,309.2,337.4
XS GIS Cut Line= 2
     1741938.517      462267.625     1742592.683      462502.347
#Sta/Elev= 30
       0  663.65    19.6  655.29    58.7  642.97    97.9  633.02   117.5  629.21
   146.8  626.14   195.8  623.53   264.3   623.7   303.4  623.13   313.2  622.58
   342.6  619.46   352.4   616.5     372  606.71   391.6   599.5   411.1  590.11
   420.9   588.6   430.7   588.5   489.4   588.8   499.2  590.75     509  595.91
   538.4  619.75   548.2  625.21     558  626.87   567.8  627.56   577.5  631.26
   597.1  642.31   606.9  648.64   636.3  669.51   646.1   675.9     695   700.5
#Mann= 3 , 0 , 0
       0      .1       0   411.1    .045       0   499.2      .1       0
Bank Sta=411.1,499.2
XS Rating Curve= 0 ,0
Exp/Cntr=0.3,0.1

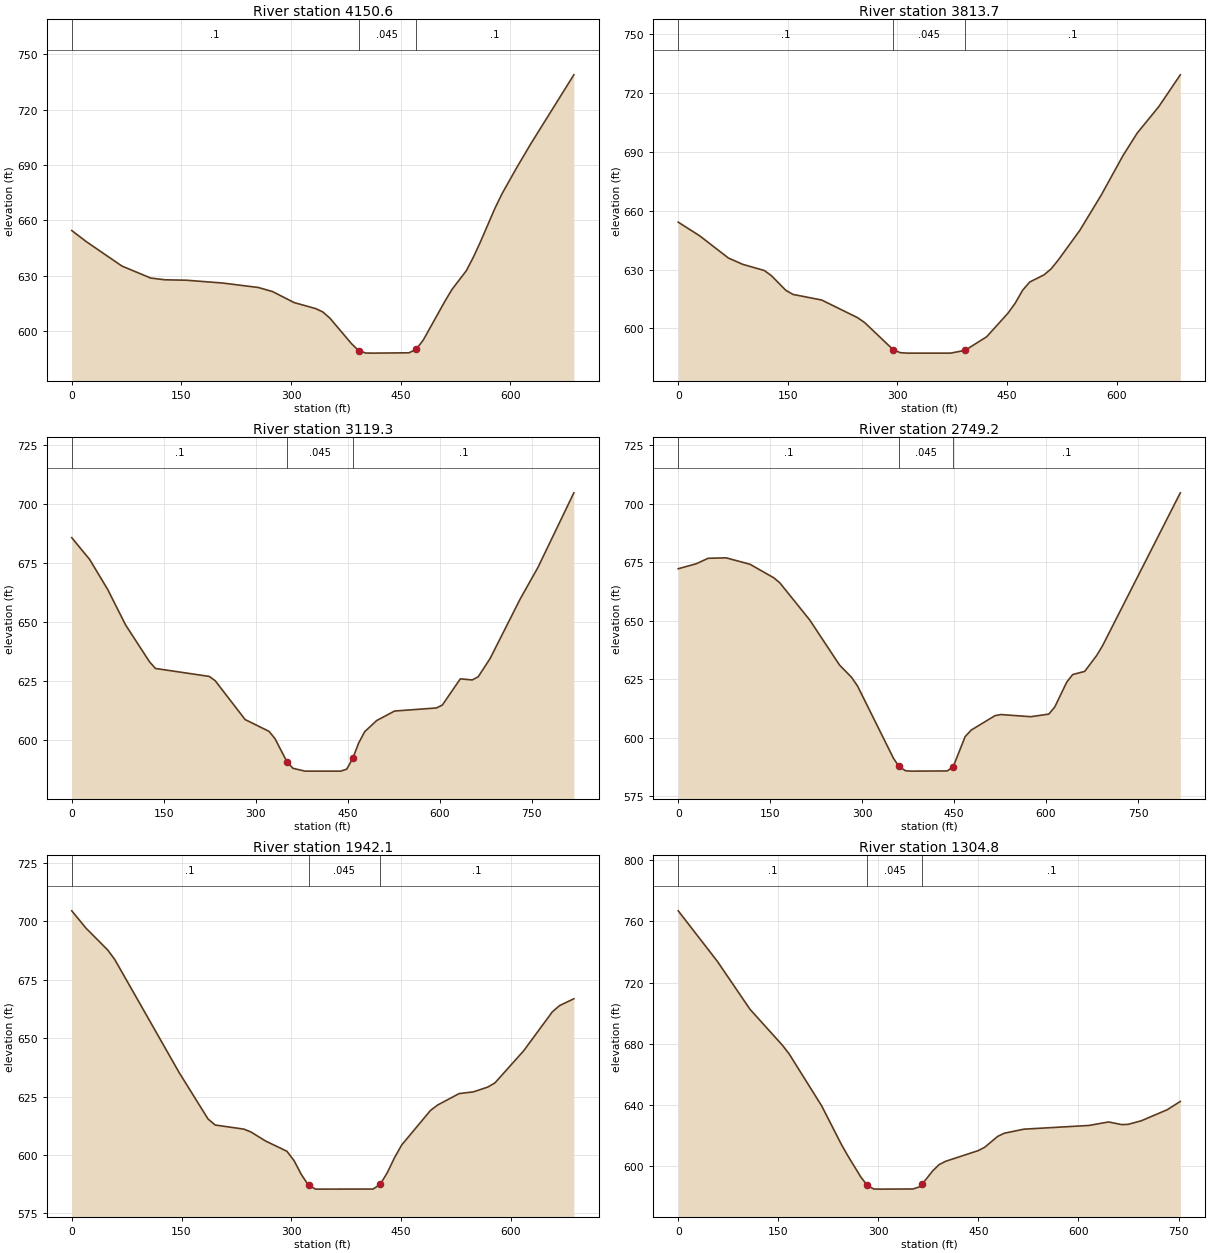
Type RM Length L Ch R = 1 ,4150.6  ,344.3,336.9,332
XS GIS Cut Line= 2
     1741876.037      462364.652     1742364.399      462847.834
#Sta/Elev= 30
       0  654.46    19.6  648.52    68.7  635.21     108  628.73   127.6  627.78
     157  627.55   206.1  626.04   255.2  623.62   274.8   621.4   304.2  615.45
   333.7  612.19   343.5  610.36   353.3  606.97   382.8  593.16   392.6   589.4
   402.4   588.1   412.2  588.06   461.3  588.24   471.1  590.04   480.9  595.11
   510.3  615.96   520.2  622.53   539.8  632.66   549.6  640.09   559.4  648.51
     579  666.48   588.8  674.45   608.5   688.3   628.1  701.44     687  738.81
#Mann= 3 , 0 , 0
       0      .1       0   392.6    .045       0   471.1      .1       0
Bank Sta=392.6,471.1
XS Rating Curve= 0 ,0
Exp/Cntr=0.3,0.1

Type RM Length L Ch R = 1 ,3813.7  ,638.1,694.4,748.2
XS GIS Cut Line= 2
     1741613.537      462520.902     1742101.899      463004.084
#Sta/Elev= 30
       0  654.22    29.4  647.25    68.7  635.91    88.3   632.7   117.8  629.56
   127.6  626.89   147.2  619.45     157  617.36   196.3   614.5   245.4  605.49
   255.2  602.96   294.4  589.05   304.2   587.6     314   587.4   372.9   587.4
   392.6  588.85     422  595.74   451.4  607.87   461.3  613.01   471.1  619.42
   480.9  623.67   500.5  627.34   510.3  630.41   520.2     635   549.6   650.1
     579  668.18   608.5  688.16   628.1  699.73   657.6   713.2     687  729.41
#Mann= 3 , 0 , 0
       0      .1       0   294.4    .045       0   392.6      .1       0
Bank Sta=294.4,392.6
XS Rating Curve= 0 ,0
Exp/Cntr=0.3,0.1

Type RM Length L Ch R = 1 ,3119.3  ,384.8,370.1,355.4
XS GIS Cut Line= 3
     1741148.528      462422.783     1741167.591      462831.876
     1741185.947      463240.928
#Sta/Elev= 30
       0  685.64    29.2  676.44    58.5  663.82    87.8  648.78   126.8  633.22
   136.5  630.38   224.3  627.02     234   625.2   282.8  608.79   321.8   603.8
   331.5  600.74     351  590.95   360.8   588.2   380.3     587   438.8     587
   448.5  587.84   458.3  592.34     468  598.88   477.8  603.65   497.3  608.36
   526.5  612.39   594.8  613.69   604.5  614.92   633.8  625.99   653.3  625.53
     663  626.87   682.5  634.64   731.3  659.65   760.5  673.12     819   704.6
#Mann= 3 , 0 , 0
       0      .1       0     351    .045       0   458.3      .1       0
Bank Sta=351,458.3
XS Rating Curve= 0 ,0
Exp/Cntr=0.3,0.1

Type RM Length L Ch R = 1 ,2749.2  ,806.9,807.1,807.3
XS GIS Cut Line= 3
     1740694.803      462503.645     1740804.737      462898.112
     1740914.671       463292.58
#Sta/Elev= 30
       0  672.16    29.2  674.27    48.8  676.62      78  676.82     117  674.08
     156  668.27   165.8  666.12   214.5  650.27   263.2     631   282.8  625.75
   292.5  622.06     351  591.24   359.5  587.87   370.5  585.88   380.2   585.7
   438.8  585.78   448.5  587.56     468  600.43   477.8  603.21   516.8  609.41
   526.5  609.87   575.2  608.95   604.5  610.06   614.2   613.1   633.8  623.74
   643.5  626.97     663   628.3   682.5  635.07   692.2  639.29     819  704.59
#Mann= 3 , 0 , 0
       0      .1       0   359.5    .045       0   448.5      .1       0
Bank Sta=359.5,448.5
XS Rating Curve= 0 ,0
Exp/Cntr=0.3,0.1

Type RM Length L Ch R = 1 ,1942.1  ,676.1,637.2,598
XS GIS Cut Line= 2
     1739940.947      462799.222     1740123.239      463460.681
#Sta/Elev= 30
       0  704.52    19.6  697.05      49  687.81    58.8  683.66     147  635.16
   186.2  615.44     196  612.84   235.2  611.08     245  609.84   264.6  606.04
     294   601.6   303.8  597.59   313.6  591.72   323.5  587.04   333.3   585.4
   411.7  585.43   421.5  587.42   431.3  592.51   441.1  598.89   450.9  604.32
   490.1  619.05   499.9  621.39   529.3  626.29   548.9  627.03   568.5  629.09
   578.3  630.87   617.5   644.6   656.7  661.28   666.5  663.94   686.1  666.88
#Mann= 3 , 0 , 0
       0      .1       0   323.5    .045       0   421.5      .1       0
Bank Sta=323.5,421.5
XS Rating Curve= 0 ,0
Exp/Cntr=0.3,0.1

Type RM Length L Ch R = 1 ,1304.8  ,435.2,417.1,398.9
XS GIS Cut Line= 2
     1739214.211      463179.084     1739788.864      463665.195
#Sta/Elev= 30
       0  766.86    58.6  733.93   107.5  702.64   156.4  679.02   166.2  673.52
     215  639.58   244.4  614.53   254.2  607.02   273.7  593.13   283.5  587.61
   293.2  585.28     303   585.2   351.9   585.3   361.7  586.68   365.9  588.58
   381.2  596.96     391  601.18   400.8  603.36   449.6  610.32   459.4  612.52
     479  619.65   488.8  621.68   518.1  624.33   615.8  626.76   645.2  629.05
   664.7  627.31   674.5   627.5     694  629.77   733.1  637.03   752.7  642.44
#Mann= 3 , 0 , 0
       0      .1       0   283.5    .045       0   365.9      .1       0
Bank Sta=283.5,365.9
XS Rating Curve= 0 ,0
Exp/Cntr=0.3,0.1

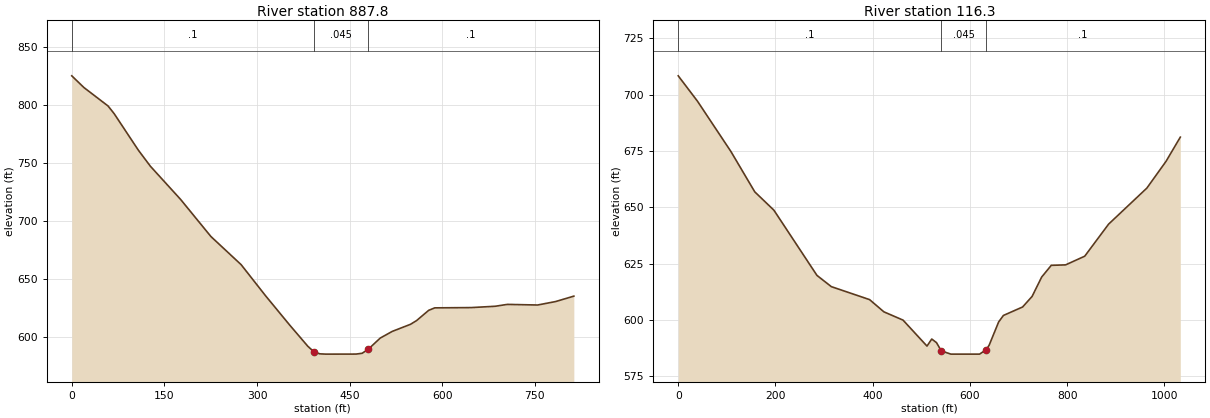
Type RM Length L Ch R = 1 ,887.8   ,783.2,771.5,752.1
XS GIS Cut Line= 2
     1738842.649      463555.062     1739584.315      463888.396
#Sta/Elev= 30
       0  825.38    19.6  815.31    58.8  799.34    68.6  792.76   107.8  761.25
   127.4  747.31   176.3  718.69   225.3  686.73   274.3   662.4   313.5   635.8
   352.7  610.42   382.1   592.1   391.9  587.34   401.7  585.45   411.5   585.2
   460.4  585.24   470.2  585.92     480  589.35   499.6  599.08   519.2  604.86
   548.6  610.94   558.4  614.15     578  622.98   587.8  625.13   646.6  625.36
   685.8  626.51   705.4  628.12   754.4  627.59   783.7  630.58   813.1  635.25
#Mann= 3 , 0 , 0
       0      .1       0   391.9    .045       0     480      .1       0
Bank Sta=391.9,480
XS Rating Curve= 0 ,0
Exp/Cntr=0.3,0.1

Type RM Length L Ch R = 1 ,116.3   ,78.1,116.3,162
XS GIS Cut Line= 3
     1738854.109      463956.114     1738952.479      464458.128
     1739468.379      464530.858
#Sta/Elev= 30
       0  708.33    39.4  697.12   108.2  674.79   157.4  656.83   196.8  648.68
   285.3  619.75   314.8  614.76   393.5     609     423  603.57   462.4  599.89
   511.6  588.37   521.4   591.5   531.2  589.89     541  586.24   560.7   584.8
   619.7   584.8   632.8  586.67   639.4  588.74     659  599.08   668.8  601.97
   708.2  605.72   727.8  610.42   747.5  619.02   767.2  624.21   796.6  624.41
     836  628.26   885.1  642.49   963.8   658.5  1003.1  670.33  1032.6  681.11
#Mann= 3 , 0 , 0
       0      .1       0     541    .045       0   632.8      .1       0
Bank Sta=541,632.8
XS Rating Curve= 0 ,0
Exp/Cntr=0.3,0.1

Chan Stop Cuts=-1
Use User Specified Reach Order=0
Composite Channel Slope=5